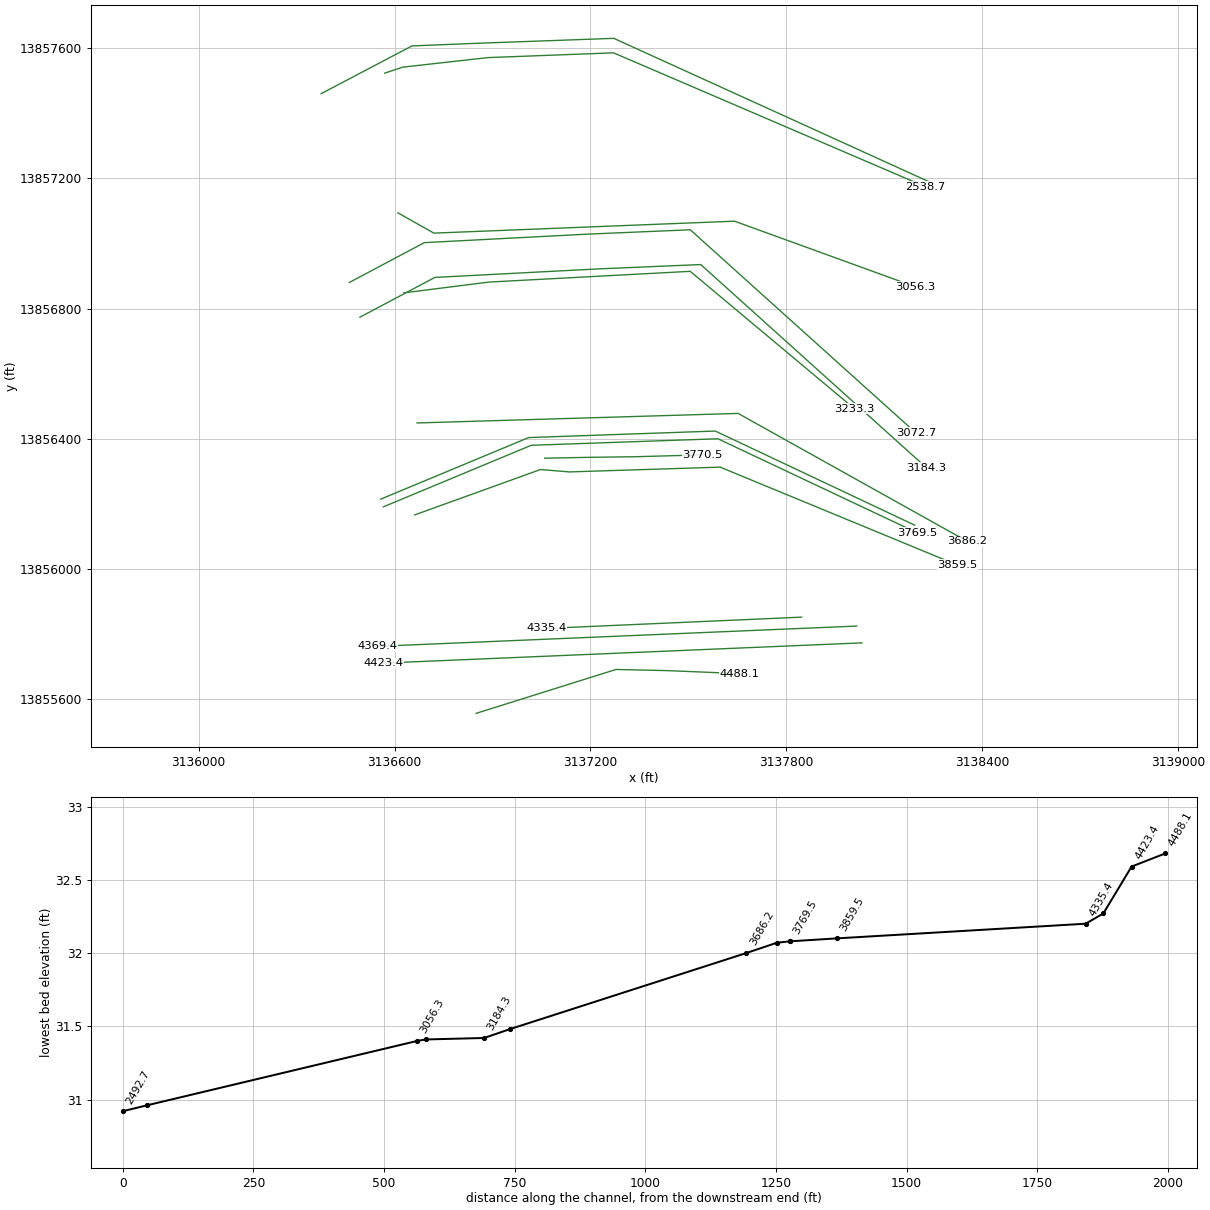
--- H110-00-00.PRJ (project) ---

Proj Title=H110-00-00
Current Plan=p03
Default Exp/Contr=.3,.1
English Units
Geom File=g01
Flow File=f01
Flow File=f03
Plan File=p01
Plan File=p03
Y Axis Title=Elevation
X Axis Title(PF)=Main Channel Distance
X Axis Title(XS)=Station
BEGIN DESCRIPTION:
Hunting Bayou Watershed
Tributary 12.70 to Hunting Bayou
HCFCD Unit H110-00-00
Flood Hazard Model
10, 2, 1, 0.2% Event
Filename H110-00-00.prj
Prepared by:  Watershed Concepts  Date: 06/04/02
Reviewed by:                      Date:
STATUS FINAL
END DESCRIPTION:
DSS Export Rating Curves= 0
DSS Export Rating Curve Sorted= 0
DSS Export Volume Flow Curves= 0
DXF OffsetX= 0
DXF OffsetY= 0
DXF ScaleX= 1
DXF ScaleY= 10

--- H110-00-00.p03 (plan) ---

Plan Title=Floodway
Version=Version 3.0.1  Mar 2001
Short Identifier=Floodway0607
Geom File=g01
Flow File=f03
Subcritical Flow
K Sum by GR= 0
Std Step Tol= 0.01
Critical Tol= 0.01
Num of Std Step Trials= 20
Max Error Tol= 0.3
Flow Tol Ratio= 0.001
Split Flow NTrial= 30
Split Flow Tol= 0.02
Split Flow Ratio= 0.02
Log Output Level= 0
Friction Slope Method= 1
Unsteady Friction Slope Method= 2
Parabolic Critical Depth
Global Vel Dist= 0 , 0 , 0
Global Log Level= 0
CheckData=True
Encroach Param=-1 ,0,0, 2
Encroach River=H110-00-00
Encroach Reach=Reach - 1
Encroach Node=4488.1
       1  4985.4  5009.3
Encroach Node=4423.4
       1  4983.1  5015.4
Encroach Node=4396.4
       1  4983.1  5015.4
Encroach Node=4369.4
       1  4983.1  5015.4
Encroach Node=4335.4
       1  4985.4  5022.2
Encroach Node=3859.5
       1 4983.97 5016.47
Encroach Node=3770.5
       1 4983.97 5016.47
Encroach Node=3769.5
       1    4984  5016.5
Encroach Node=3757.0
       1    4984  5016.5
Encroach Node=3744.5
       1    4984  5016.5
Encroach Node=3686.2
       1    4984  5016.5
Encroach Node=3233.3
       1  4984.9    5019
Encroach Node=3184.3
       1  4984.9    5019
Encroach Node=3128.5
       1  4984.9    5019
Encroach Node=3072.7
       1  4984.9    5019
Encroach Node=3056.3
       1  4984.9    5019
Encroach Node=2538.7
       1  4984.1  5017.2
Encroach Node=2492.7
       1  4984.1  5017.2
Encroach Node=2466.9
       1  4984.1  5017.2
Encroach Node=2441.1
       1  4984.1  5017.2
Encroach Node=2391.7
       1 4984.09 5016.49
Encroach Node=1876.1
       1  4977.3  5014.6
Encroach Node=1811.3
       1  4977.3  5014.6
Encroach Node=1789.6
       1  4977.3  5014.6
Encroach Node=1767.9
       1  4977.3  5014.6
Encroach Node=1766.6
       1 4983.95 5016.05
Encroach Node=1756.1
       1 4983.95 5016.05
Encroach Node=1536.7
       1 4983.95 5016.05
Encroach Node=1136.8
       1  4983.5  5017.2
Encroach Node=1022.0
       1  4983.5  5017.2
Encroach Node=1010.0
       1  4983.5  5020.7
Encroach Node=998.0
       1  4983.5  5017.2
Encroach Node=997.0
       1 4982.54 5018.14
Encroach Node=572.3
       1  4986.8  5015.5
Encroach Node=456.3
       1  4986.8  5015.5
Encroach Node=434.0
       1  4986.8  5015.5
Encroach Node=411.7
       1  4986.8  5015.5
Encroach Node=406.8
       1 4982.23 5018.83
Encroach Reach=H110-00-00_0004
Encroach Node=4488.1
       1  4985.4  5009.3
Encroach Node=4423.4
       1  4983.1  5015.4
Encroach Node=4396.4
       1  4983.1  5015.4
Encroach Node=4369.4
       1  4983.1  5015.4
Encroach Node=4335.4
       1  4985.4  5022.2
Encroach Node=3859.5
       1 4983.97 5016.47
Encroach Node=3770.5
       1 4983.97 5016.47
Encroach Node=3769.5
       1    4984  5016.5
Encroach Node=3757.0
       1    4984  5016.5
Encroach Node=3744.5
       1    4984  5016.5
Encroach Node=3686.2
       1    4984  5016.5
Encroach Node=3233.3
       1  4984.9    5019
Encroach Node=3184.3
       1  4984.9    5019
Encroach Node=3128.5
       1  4984.9    5019
Encroach Node=3072.7
       1  4984.9    5019
Encroach Node=3056.3
       1  4984.9    5019
Encroach Node=2538.7
       1  4984.1  5017.2
Encroach Node=2492.7
       1  4984.1  5017.2
Encroach Node=2466.9
       1  4984.1  5017.2
Encroach Node=2441.1
       1  4984.1  5017.2
Encroach Node=2391.7
       1 4984.09 5016.49
Encroach Node=1876.1
       1  4977.3  5014.6
Encroach Node=1811.3
       1  4977.3  5014.6
Encroach Node=1789.6
       1  4977.3  5014.6
Encroach Node=1767.9
       1  4977.3  5014.6
Encroach Node=1766.6
       1 4983.95 5016.05
Encroach Node=1756.1
       1 4983.95 5016.05
Encroach Node=1536.7
       1 4983.95 5016.05
Encroach Node=1136.8
       1  4983.5  5017.2
Encroach Node=1022.0
       1  4983.5  5017.2
Encroach Node=1010.0
       1  4983.5  5020.7
Encroach Node=998.0
       1  4983.5  5017.2
Encroach Node=997.0
       1 4982.54 5018.14
Encroach Node=572.3
       1  4986.8  5015.5
Encroach Node=456.3
       1  4986.8  5015.5
Encroach Node=434.0
       1  4986.8  5015.5
Encroach Node=411.7
       1  4986.8  5015.5
Encroach Node=406.8
       1 4982.23 5018.83
Computation Interval=1HOUR
Output Interval=1HOUR
Run HTab= 0
Run UNet= 0
Run PostProcess= 0
UNET Theta= 1
UNET ZTol= 0.02
UNET ZSATol= 0.1
UNET MxIter= 20
UNET MaxInSteps= 20
UNET DtIC= 0
UNET DtMin= 0
UNET MaxCRTS= 20
UNET WFStab= 2
UNET SFStab= 1
UNET WFX= 1
UNET SFX= 1
UNET Convert EG Bridges=-1
UNET Use Existing IB Tables=-1
Instantaneous Interval=1HOUR
Write IC File= 0
Write Velocity= 0
Write Detailed= 0

--- H110-00-00.p01 (plan) ---

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Plan Title=FEMA Effective June 2007
Short Identifier=FEMAeff0607
Geom File=g01
Flow File=f01
Encroach Param=-1 ,0,0, 0

--- H110-00-00.f03 (steady flow) ---

Flow Title= Floodway
Number of Profiles= 2
Profile Names=1PCT_100yr, 1PCTFloodway_100yrFW
River Rch & RM=H110-00-00,H110-00-00_0004,4488.1
     268     268
River Rch & RM=H110-00-00,H110-00-00_0004,3128.5
     307     307
River Rch & RM=H110-00-00,H110-00-00_0004,2466.9
     419     419
River Rch & RM=H110-00-00,H110-00-00_0004,1811.3
     536     536
River Rch & RM=H110-00-00,H110-00-00_0004,1010
     602     602
River Rch & RM=H110-00-00,H110-00-00_0004,456.3
     635     635
Boundary for River Rch & Prof#=H110-00-00,H110-00-00_0004, 1
Up Type= 0
Dn Type= 3
Dn Slope= 0.00040
Boundary for River Rch & Prof#=H110-00-00,H110-00-00_0004, 2
Up Type= 0
Dn Type= 3
Dn Slope= 0.00040

--- H110-00-00.f01 (steady flow) ---

Flow Title= FEMA Effective June 2007
Number of Profiles= 4
Profile Names=10PCT_10yr, 2PCT_50yr, 1PCT_100yr, 0.2PCT_500yr
River Rch & RM=H110-00-00,H110-00-00_0004,4488.1
     147     226     268     393
River Rch & RM=H110-00-00,H110-00-00_0004,3128.5
     169     259     307     450
River Rch & RM=H110-00-00,H110-00-00_0004,2466.9
     230     353     419     614
River Rch & RM=H110-00-00,H110-00-00_0004,1811.3
     295     452     536     786
River Rch & RM=H110-00-00,H110-00-00_0004,1010
     331     508     602     882
River Rch & RM=H110-00-00,H110-00-00_0004,456.3
     349     535     635     930
Boundary for River Rch & Prof#=H110-00-00,H110-00-00_0004, 1
Up Type= 0
Dn Type= 3
Dn Slope= 0.00040
Boundary for River Rch & Prof#=H110-00-00,H110-00-00_0004, 2
Up Type= 0
Dn Type= 3
Dn Slope= 0.00040
Boundary for River Rch & Prof#=H110-00-00,H110-00-00_0004, 3
Up Type= 0
Dn Type= 3
Dn Slope= 0.00040
Boundary for River Rch & Prof#=H110-00-00,H110-00-00_0004, 4
Up Type= 0
Dn Type= 3
Dn Slope= 0.00040

--- H110-00-00.g01 (geometry) ---

Geom Title=H110-00-00 June 2007

River Reach=H110-00-00,H110-00-00_0004
Reach XY= 33
      3137368.09     13855689.12      3137332.22     13855747.72
      3137308.62     13855824.06      3137301.78     13855869.49
      3137295.69     13855948.65      3137295.69     13856100.87
      3137295.69     13856313.97       3137265.5        13856403
      3137184.45     13856582.42         3137140        13856739
      3137089.48     13856883.15         3137077        13856961
      3137063.75        13857005      3137051.25        13857058
      3137010.75        13857194      3136989.75        13857356
       3136966.5        13857620      3136954.06      13857690.4
      3136932.96     13857876.82      3136950.75        13857941
         3136974        13858041      3137050.79     13858193.39
      3137092.75        13858283      3137164.75        13858444
       3137226.7     13858583.38      3137268.72     13858680.35
      3137310.74     13858790.26      3137320.44     13858890.46
         3137323        13859019      3137310.74      13859142.6
      3137313.97     13859288.06      3137349.53     13859427.05
      3137421.88      13859610.9      3137457.25     13859730.59
       3137502.6     13859865.85      3137546.62     13859993.74

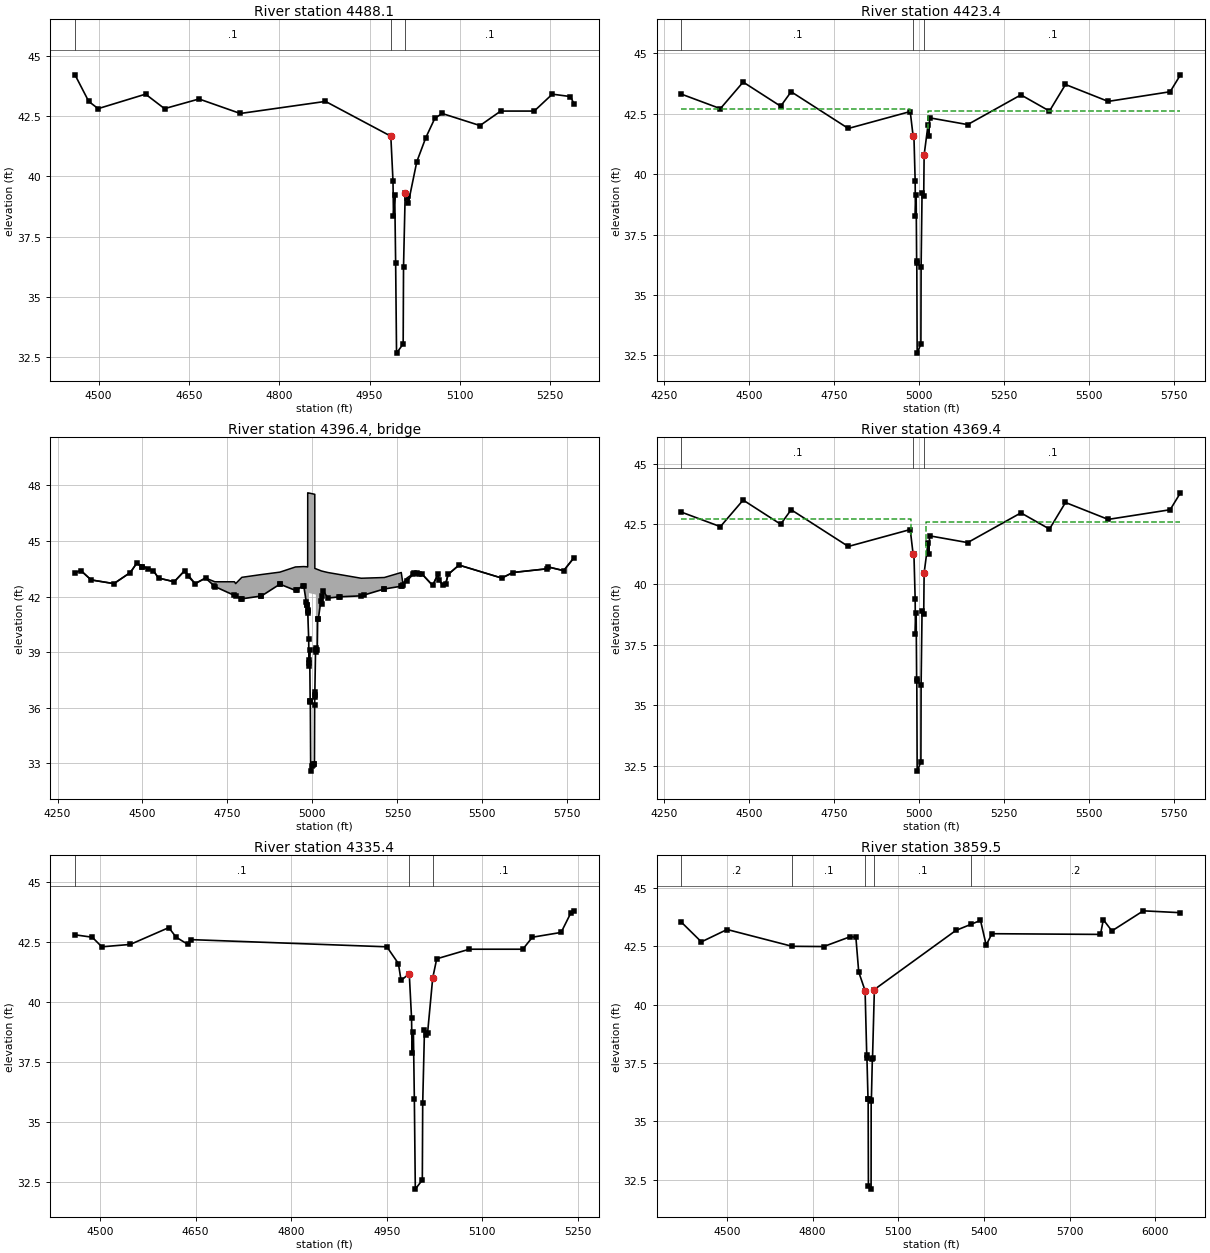
Type RM Length L Ch R = 1 ,4488.1,65.2,64.7,63.2
XS GIS Cut Line= 4
      3136849.75     13855556.26      3137278.24     13855691.18
      3137438.69     13855687.54      3137657.49     13855678.42
BEGIN DESCRIPTION:
Cross Section 4488.1
END DESCRIPTION:
#Sta/Elev= 30
  4460.9    44.2  4483.7    43.1  4499.3    42.8  4578.1    43.4  4609.6    42.8
  4666.9    43.2  4735.4    42.6  4876.9    43.1  4985.4   41.66    4989   39.81
  4989.8   38.36  4991.9   39.23  4993.4   36.42  4994.9   32.68  5005.9   33.06
  5006.5   36.26  5009.3   39.32  5011.6   39.09  5014.2    39.2  5014.5    38.9
  5028.5    40.6  5043.5    41.6  5058.5    42.4  5070.6    42.6  5133.5    42.1
  5167.9    42.7  5223.6    42.7  5253.6    43.4  5283.7    43.3  5289.6      43
#Mann= 3 , 1 , 0
 4460.90     0.1       0  4985.4    0.02       0  5009.3     0.1       0
Bank Sta=4985.40,5009.30
Exp/Cntr=0.5,0.3

Type RM Length L Ch R = 1 ,4423.4,54,54,54
XS GIS Cut Line= 2
      3138031.55     13855772.94      3136564.67     13855710.70
BEGIN DESCRIPTION:
Upstream Section of Bridge/Culvert/Weir
END DESCRIPTION:
#Sta/Elev= 30
  4301.4   43.31  4415.9   42.71  4482.9   43.81  4593.3   42.81  4624.1   43.41
  4792.3   41.89  4974.5   42.59  4983.1   41.56  4985.4   41.57    4989   39.72
  4989.8   38.27  4991.9   39.14  4993.4   36.33  4993.8   36.39  4994.9   32.59
  5005.9   32.97  5006.5   36.17  5009.3   39.23  5014.2   39.11  5015.4   40.79
  5026.8   42.03  5029.5   41.59  5031.5   42.33  5143.5   42.05  5300.2   43.28
  5384.2   42.61  5431.3   43.71  5556.9   43.01  5739.2   43.41  5769.6   44.11
#Mann= 3 , 1 , 0
 4301.40     0.1       0  4983.1    0.02       0  5015.4     0.1       0
#XS Ineff= 2 , 0
       0  4973.1    42.7  5025.4       0    42.6
Bank Sta=4983.10,5015.40
Exp/Cntr=0.5,0.3

Type RM Length L Ch R = 3 ,4396.4,,,
BEGIN DESCRIPTION:
CRANE STREET
Structure ID: H10-15
END DESCRIPTION:
Bridge Culvert--1,0,-1,-1, 0
Deck Dist Width WeirC Skew NumUp NumDn MinLoCord MaxHiCord MaxSubmerge Is_Ogee
10,34,2.6,, 60, 60,,,0.95,0,1,1,,
  4301.4    4319  4348.8  4415.9  4464.3  4482.9  4531.8  4547.2  4593.3  4624.1
  4654.8  4685.6    4713  4770.7    4774  4792.3  4849.8  4904.2  4950.3  4974.5
  4983.1  4985.4 4985.99  4986.1 4986.21    4989 4989.61  4989.7    5007 5007.11
 5010.19  5010.3  5011.6  5014.2  5015.4  5017.3  5026.8  5029.5  5031.5  5045.3
  5143.5  5211.5  5261.4  5266.2    5278  5300.2  5323.3  5353.8    5369  5372.8
  5384.2  5392.2  5399.4  5431.3  5556.9  5589.9  5690.1  5693.6  5739.2  5769.6
    43.3    43.4    42.9    42.7    43.3    43.8    43.4      43    42.8    43.4
    42.7      43    42.8    42.8    42.7   43.04   43.19   43.32    43.6   43.62
   43.61    43.6    43.6    47.6    47.6   47.59   47.59   47.59   47.52   43.52
    43.5    43.5   43.49   43.47   43.46   43.45   43.38   43.37   43.36    43.3
   42.99   43.03    43.3    42.7      43   43.28    43.2    42.6    43.2    42.9
    42.6    42.7    43.2    43.7      43    43.3    43.5    43.6    43.4    44.1
    43.3    43.4    42.9    42.7    43.3    43.8    43.4      43    42.8    43.4
    42.7      43   42.54   42.06   42.03   41.88   42.03   42.67   42.33   42.58
   41.55   41.56   41.26    41.2   41.14   39.71    38.6   42.19   42.12   42.12
    42.1   39.12   38.99    39.1   40.78   40.79   42.02   41.58   42.32   41.92
   42.04   42.41   42.56   42.63   42.85   43.27    43.2    42.6    43.2    42.9
    42.6    42.7    43.2    43.7      43    43.3    43.5    43.6    43.4    44.1
  4301.4    4319  4348.8  4415.9  4464.3  4482.9  4531.8  4547.2  4593.3  4624.1
  4654.8  4685.6    4713  4770.7    4774  4792.3  4849.8  4904.2  4950.3  4974.5
  4983.1  4985.4 4985.99  4986.1 4986.21    4989 4989.61  4989.7    5007 5007.11
 5010.19  5010.3  5011.6  5014.2  5015.4  5017.3  5026.8  5029.5  5031.5  5045.3
  5143.5  5211.5  5261.4  5266.2    5278  5300.2  5323.3  5353.8    5369  5372.8
  5384.2  5392.2  5399.4  5431.3  5556.9  5589.9  5690.1  5693.6  5739.2  5769.6
    43.3    43.4    42.9    42.7    43.3    43.8    43.4      43    42.8    43.4
    42.7      43    42.8    42.8    42.7   43.04   43.19   43.32    43.6   43.62
   43.61    43.6    43.6    47.6    47.6   47.59   47.59   47.59   47.52   43.52
    43.5    43.5   43.49   43.47   43.46   43.45   43.38   43.37   43.36    43.3
   42.99   43.03    43.3    42.7      43   43.28    43.2    42.6    43.2    42.9
    42.6    42.7    43.2    43.7      43    43.3    43.5    43.6    43.4    44.1
   43.01   43.11   42.61   42.41   43.01   43.51   43.11   42.71   42.51   43.11
   42.41   42.71   42.25   41.77   41.74   41.59   41.74   42.38   42.04   42.29
   41.26   41.27   40.97   40.91   40.85   39.42   38.31    41.9   41.83   41.83
   41.81   38.83    38.7   38.81   40.49    40.5   41.73   41.29   42.03   41.63
   41.75   42.12   42.27   42.34   42.56   42.98   42.91   42.31   42.91   42.61
   42.31   42.41   42.91   43.41   42.71   43.01   43.21   43.31   43.11   43.81
Abutment Skew #Up #Dn=, 2 , 2
 4989.50 4993.80
   42.19   36.38
 4989.50 4993.80
   41.90   36.09
Abutment Skew #Up #Dn=, 2 , 2
 5005.50 5010.39
   32.95   42.10
 5005.50 5010.39
   32.66   41.81
BR Coef= 1 , 1 , 0 ,1.25, 0 ,,,0.8,0,2,0,
Wspro=,,,, 1 ,,,, 0 ,,,, 0 ,,,,-1 ,-1 ,-1 , 0 , 0 , 0 , 0 , 0
BC Design=,, 0 ,, 0 ,,,,,,
BR U #Sta/Elev= 93
  4301.4    43.3    4319    43.4  4348.8    42.9  4415.9    42.7  4464.3    43.3
  4482.9    43.8  4497.9    43.6  4499.7    43.6    4516    43.5  4531.8    43.4
  4547.2      43  4593.3    42.8  4624.1    43.4  4633.7    43.1  4654.8    42.7
  4685.6      43  4709.9   42.59    4713   42.54  4770.7   42.06    4774   42.03
  4790.5   41.89  4792.3   41.88  4849.5   42.03  4849.8   42.03  4903.4   42.66
  4904.2   42.67  4950.3   42.33  4953.7   42.37  4971.6   42.57  4974.5   42.58
  4981.7   41.72  4983.1   41.55  4985.4   41.56 4985.99   41.26  4986.1    41.2
 4986.21   41.14    4989   39.71 4989.61    38.6  4989.7   38.44  4989.8   38.26
  4991.9   39.13  4993.4   36.32  4993.7   36.37  4993.8   36.38  4994.9   32.58
  4999.6   32.87  5002.3   32.91  5005.5   32.95  5005.9   32.96  5006.5   36.16
 5006.89   36.59    5007   36.71 5007.11   36.83  5009.3   39.22 5010.19   39.13
  5010.3   39.12  5011.6   38.99  5014.2    39.1  5015.4   40.78  5017.3   40.79
  5024.8   41.76  5026.8   42.02  5029.5   41.58  5031.5   42.32  5045.3   41.92
  5077.2   41.98  5082.3   41.99  5143.5   42.04  5151.3   42.08  5211.1   42.41
  5211.5   42.41  5261.4   42.56  5262.3   42.56  5266.2   42.63    5278   42.85
  5296.2    43.2  5300.2   43.27  5306.9   43.25  5312.1   43.23  5323.3    43.2
  5353.8    42.6    5369    43.2  5372.8    42.9  5384.2    42.6  5392.2    42.7
  5399.4    43.2  5431.3    43.7  5556.9      43  5589.9    43.3  5690.1    43.5
  5693.6    43.6  5739.2    43.4  5769.6    44.1
BR U #Mann= 3
 4301.40     0.1  4983.1    0.02  5015.4     0.1
BR U Banks=4983.10,5015.40
BR D #Sta/Elev= 93
  4301.4   43.01    4319   43.11  4348.8   42.61  4415.9   42.41  4464.3   43.01
  4482.9   43.51  4497.9   43.31  4499.7   43.31    4516   43.21  4531.8   43.11
  4547.2   42.71  4593.3   42.51  4624.1   43.11  4633.7   42.81  4654.8   42.41
  4685.6   42.71  4709.9    42.3    4713   42.25  4770.7   41.77    4774   41.74
  4790.5    41.6  4792.3   41.59  4849.5   41.74  4849.8   41.74  4903.4   42.37
  4904.2   42.38  4950.3   42.04  4953.7   42.08  4971.6   42.28  4974.5   42.29
  4981.7   41.43  4983.1   41.26  4985.4   41.27 4985.99   40.97  4986.1   40.91
 4986.21   40.85    4989   39.42 4989.61   38.31  4989.7   38.15  4989.8   37.97
  4991.9   38.84  4993.4   36.03  4993.7   36.08  4993.8   36.09  4994.9   32.29
  4999.6   32.58  5002.3   32.62  5005.5   32.66  5005.9   32.67  5006.5   35.87
 5006.89    36.3    5007   36.42 5007.11   36.54  5009.3   38.93 5010.19   38.84
  5010.3   38.83  5011.6    38.7  5014.2   38.81  5015.4   40.49  5017.3    40.5
  5024.8   41.47  5026.8   41.73  5029.5   41.29  5031.5   42.03  5045.3   41.63
  5077.2   41.69  5082.3    41.7  5143.5   41.75  5151.3   41.79  5211.1   42.12
  5211.5   42.12  5261.4   42.27  5262.3   42.27  5266.2   42.34    5278   42.56
  5296.2   42.91  5300.2   42.98  5306.9   42.96  5312.1   42.94  5323.3   42.91
  5353.8   42.31    5369   42.91  5372.8   42.61  5384.2   42.31  5392.2   42.41
  5399.4   42.91  5431.3   43.41  5556.9   42.71  5589.9   43.01  5690.1   43.21
  5693.6   43.31  5739.2   43.11  5769.6   43.81
BR D #Mann= 3
 4301.40     0.1  4983.1    0.02  5015.4     0.1
BR D Banks=4983.10,5015.40

Type RM Length L Ch R = 1 ,4369.4,34,34,34
XS GIS Cut Line= 2
      3138015.60     13855824.53      3136548.72     13855762.29
BEGIN DESCRIPTION:
Downstream Section of Bridge/Culvert/Weir
END DESCRIPTION:
#Sta/Elev= 30
  4301.4   42.99  4415.9   42.39  4482.9   43.49  4593.3   42.49  4624.1   43.09
  4792.3   41.57  4974.5   42.27  4983.1   41.24  4985.4   41.25    4989    39.4
  4989.8   37.95  4991.9   38.82  4993.4   36.01  4993.8   36.07  4994.9   32.27
  5005.9   32.65  5006.5   35.85  5009.3   38.91  5014.2   38.79  5015.4   40.47
  5026.8   41.71  5029.5   41.27  5031.5   42.01  5143.5   41.73  5300.2   42.96
  5384.2   42.29  5431.3   43.39  5556.9   42.69  5739.2   43.09  5769.6   43.79
#Mann= 3 , 1 , 0
 4301.40     0.1       0  4983.1    0.02       0  5015.4     0.1       0
#XS Ineff= 2 , 0
       0 4976.43    42.7 5022.07       0    42.6
Bank Sta=4983.10,5015.40
Exp/Cntr=0.5,0.3

Type RM Length L Ch R = 1 ,4335.4,478.9,475.9,472.5
XS GIS Cut Line= 2
      3137846.59     13855851.93      3137064.35     13855817.29
BEGIN DESCRIPTION:
Cross Section 4335.4
END DESCRIPTION:
#Sta/Elev= 30
  4460.9    42.8    4488    42.7    4503    42.3  4547.7    42.4  4608.1    43.1
  4619.6    42.7  4638.1    42.4  4642.6    42.6  4950.3    42.3  4968.4    41.6
  4972.5    40.9  4985.4   41.18    4989   39.33  4989.8   37.88  4991.9   38.75
  4993.4   35.94  4994.9    32.2  5005.9   32.58  5006.5   35.78  5009.3   38.84
  5011.6   38.61  5014.2   38.72  5022.2      41  5028.5    41.8  5079.7    42.2
  5163.6    42.2  5178.6    42.7  5223.7    42.9  5238.7    43.7  5243.9    43.8
#Mann= 3 , 1 , 0
 4460.90     0.1       0  4985.4    0.02       0  5022.2     0.1       0
Bank Sta=4985.40,5022.20
Exp/Cntr=0.3,0.1

Type RM Length L Ch R = 1 ,3859.5,73.5,89,80.9
XS GIS Cut Line= 5
      3136661.75     13856166.08      3137046.95     13856305.49
      3137135.00     13856298.15      3137597.24     13856312.82
      3138323.61     13856012.00
BEGIN DESCRIPTION:
Cross Section 3859.5 - Interpolated
END DESCRIPTION:
#Sta/Elev= 30
  4341.2   43.53  4410.9   42.69  4500.9   43.22  4728.5    42.5  4839.2   42.49
  4931.7   42.91  4951.7   42.89  4961.7    41.4 4983.97    40.6 4989.97   37.72
 4990.17   37.84 4994.17   35.98 4994.67   35.97 4995.57   32.22 5004.97    32.1
 5005.27    35.9 5005.87   35.86 5009.37   37.68 5009.97    37.7 5016.47   40.65
  5301.7   43.18  5354.2   43.44  5387.9   43.61  5407.9   42.55  5427.9   43.04
  5807.9   43.01  5817.9   43.64  5847.9   43.16  5957.9   44.02  6087.9   43.94
#Mann= 5 , 1 , 0
 4341.20     0.2       0  4728.5     0.1       0 4983.97    0.02       0
 5016.47     0.1       0  5354.2     0.2       0
Bank Sta=4983.97,5016.47
Exp/Cntr=0.3,0.1

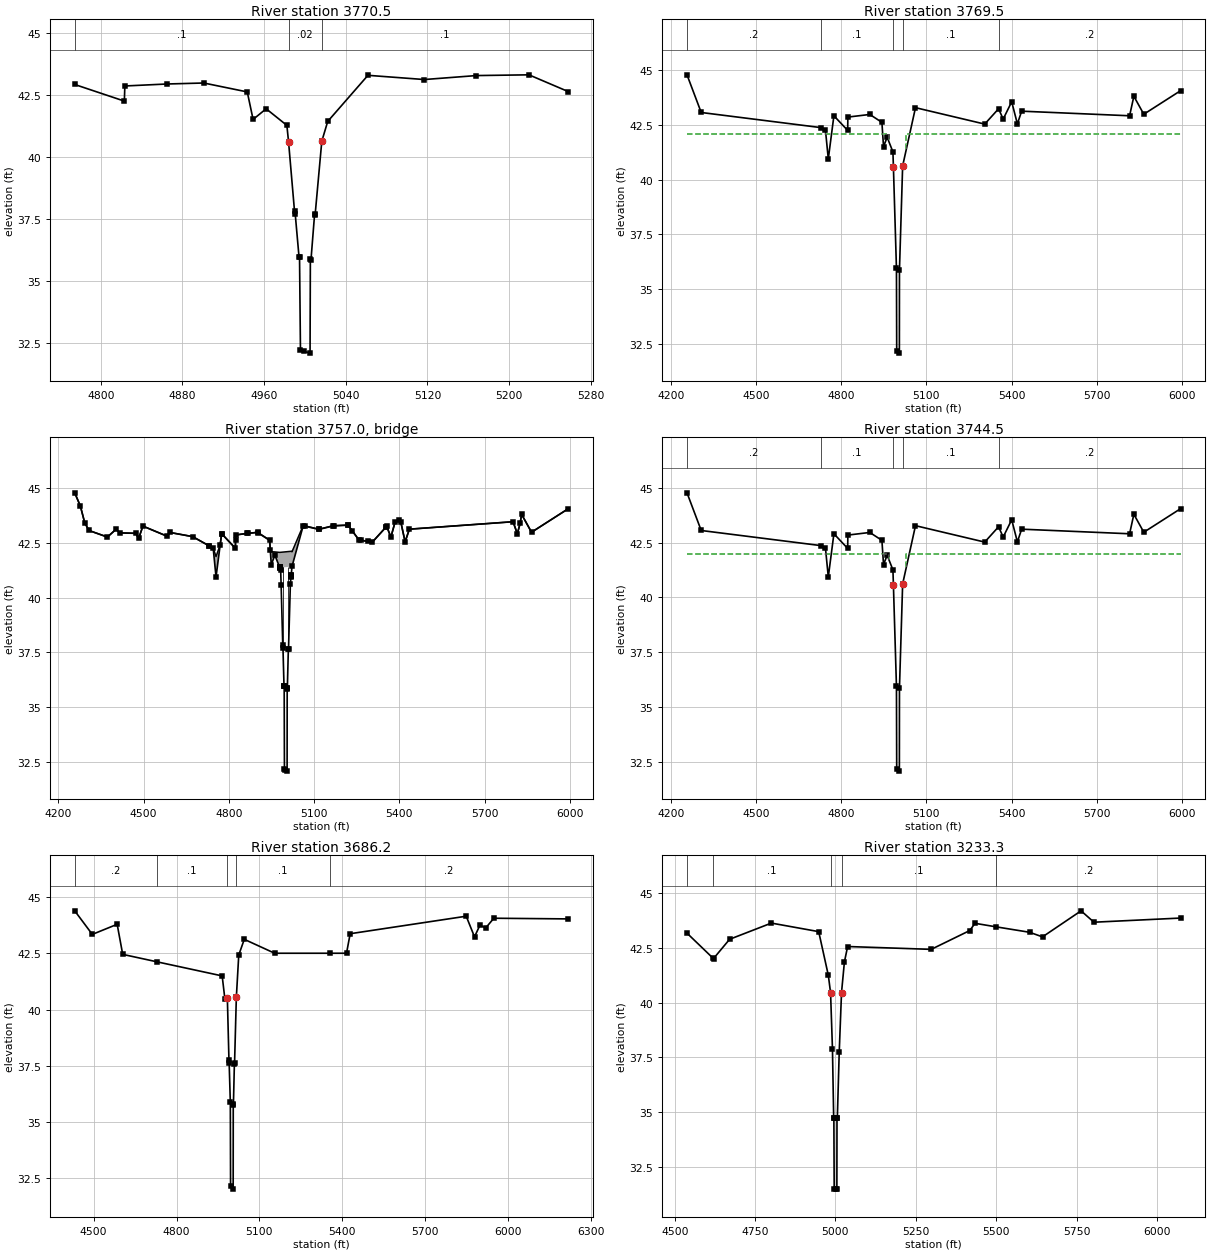
Type RM Length L Ch R = 1 ,3770.5,1,1,1
XS GIS Cut Line= 4
      3137059.97     13856340.33      3137191.28     13856342.88
      3137338.68     13856344.84      3137543.45     13856350.57
BEGIN DESCRIPTION:
Cross Section 3770.5
END DESCRIPTION:
#Sta/Elev= 28
 4774.47   42.92 4823.07   42.25 4823.57   42.86 4864.87   42.94 4900.87   42.98
 4943.47   42.62 4949.17   41.51 4961.97   41.94 4982.27   41.27 4983.97   40.58
 4989.97    37.7 4990.17   37.82 4994.17   35.96 4994.67   35.95 4995.57    32.2
 4999.27   32.15 5004.97   32.08 5005.27   35.88 5005.87   35.84 5009.37   37.66
 5009.97   37.68 5016.47   40.63 5022.27   41.43 5061.67   43.29 5116.87   43.12
 5167.77   43.28 5219.37   43.31 5258.07   42.63
#Mann= 3 , 1 , 0
 4774.47     0.1       0 4983.97    0.02       0 5016.47     0.1       0
Bank Sta=4983.97,5016.47
Exp/Cntr=0.5,0.3

Type RM Length L Ch R = 1 ,3769.5,25,25,25
XS GIS Cut Line= 4
      3136565.78     13856190.82      3137018.78     13856379.99
      3137590.29     13856400.03      3138200.55     13856111.06
BEGIN DESCRIPTION:
Upstream Section of Bridge/Culvert/Weir
END DESCRIPTION:
#Sta/Elev= 30
  4257.4   44.79  4307.4   43.07  4728.5   42.38  4744.8   42.26  4754.8   40.95
  4774.5   42.92  4823.1   42.25  4823.6   42.86  4900.9   42.98  4943.5   42.62
  4949.2   41.51    4962   41.94  4982.3   41.27    4984   40.58  4994.7   35.95
  4995.6    32.2    5005   32.08  5005.3   35.88  5016.5   40.63  5061.7   43.29
  5305.4   42.54  5354.2   43.24  5370.4   42.77  5400.4   43.56  5420.4   42.55
  5435.4   43.13  5815.4   42.92  5830.4   43.81  5865.4   42.99  5995.4   44.07
#Mann= 5 , 1 , 0
 4257.40     0.2       0  4728.5     0.1       0    4984    0.02       0
  5016.5     0.1       0  5354.2     0.2       0
#XS Ineff= 2 , 0
       0    4969    42.1    5030       0    42.1
Bank Sta=4984.00,5016.50
Exp/Cntr=0.5,0.3

Type RM Length L Ch R = 3 ,3757.0,,,
BEGIN DESCRIPTION:
MARCUS STREET
Structure ID: H10-13
END DESCRIPTION:
Bridge Culvert--1,0,-1,-1, 0
Deck Dist Width WeirC Skew NumUp NumDn MinLoCord MaxHiCord MaxSubmerge Is_Ogee
10,5,2.6,, 47, 47,,,0.95,0,1,1,,
  4257.4  4277.4  4292.4  4307.4  4372.4  4402.4  4417.4  4472.4  4482.4  4497.4
  4582.4  4592.4  4672.4  4744.8  4754.8  4769.3  4774.5  4823.1  4823.6  4900.9
  4943.5  4945.7  4949.2    4962 4979.21 5019.19  5019.3  5022.3  5061.7  5116.9
  5167.8  5219.4  5258.1  5305.4  5355.4  5370.4  5385.4  5400.4  5405.4  5420.4
  5435.4  5800.4  5815.4  5825.4  5830.4  5865.4  5995.4
   44.79   44.18   43.43   43.07   42.77   43.12   42.96   42.94   42.71   43.27
   42.81   42.98   42.79   42.27   41.88   42.41   42.93   42.26   42.87   42.99
   42.63    42.2    42.1   42.09   42.07   42.12   42.12    42.1    43.3   43.13
   43.29   43.32   42.64   42.55   43.26   42.77   43.47   43.56   43.45   42.55
   43.13   43.47   42.92    43.4   43.81   42.99   44.07
   44.79   44.18   43.43   43.07   42.77   43.12   42.96   42.94   42.71   43.27
   42.81   42.98   42.79   42.26   40.95    42.4   42.92   42.25   42.86   42.98
   42.62   42.19   41.51   41.94   41.37   41.42   41.02   41.43   43.29   43.12
   43.28   43.31   42.63   42.54   43.26   42.77   43.47   43.56   43.45   42.55
   43.13   43.47   42.92    43.4   43.81   42.99   44.07
  4257.4  4277.4  4292.4  4307.4  4372.4  4402.4  4417.4  4472.4  4482.4  4497.4
  4582.4  4592.4  4672.4  4744.8  4754.8  4769.3  4774.5  4823.1  4823.6  4900.9
  4943.5  4945.7  4949.2    4962 4979.21 5019.19  5019.3  5022.3  5061.7  5116.9
  5167.8  5219.4  5258.1  5305.4  5355.4  5370.4  5385.4  5400.4  5405.4  5420.4
  5435.4  5800.4  5815.4  5825.4  5830.4  5865.4  5995.4
   44.79   44.18   43.43   43.07   42.77   43.12   42.96   42.94   42.71   43.27
   42.81   42.98   42.79   42.27   41.88   42.41   42.93   42.26   42.87   42.99
   42.63    42.2    42.1   42.09   42.07   42.12   42.12    42.1    43.3   43.13
   43.29   43.32   42.64   42.55   43.26   42.77   43.47   43.56   43.45   42.55
   43.13   43.47   42.92    43.4   43.81   42.99   44.07
   44.79   44.18   43.43   43.07   42.77   43.12   42.96   42.94   42.71   43.27
   42.81   42.98   42.79   42.26   40.95    42.4   42.92   42.25   42.86   42.98
   42.62   42.19   41.51   41.94   41.37   41.42   41.02   41.43   43.29   43.12
   43.28   43.31   42.63   42.54   43.26   42.77   43.47   43.56   43.45   42.55
   43.13   43.47   42.92    43.4   43.81   42.99   44.07
Pier Skew, UpSta & Num, DnSta & Num=,4990.0, 2 ,4990.0, 2 , 0 , 0 , 0 ,,
       1       1
   36.68   42.38
       1       1
   36.68   42.38
Pier Skew, UpSta & Num, DnSta & Num=,5009.4, 2 ,5009.4, 2 , 0 , 0 , 0 ,,
       1       1
   36.41   42.41
       1       1
   36.41   42.41
Abutment Skew #Up #Dn=, 2 , 2
 4979.10 4994.20
   41.37   35.96
 4979.10 4994.20
   41.37   35.96
Abutment Skew #Up #Dn=, 2 , 2
 5005.90 5019.39
   35.89   41.42
 5005.90 5019.39
   35.89   41.42
BR Coef= 1 , 1 , 0 ,1.25, 0 ,,,0.8,0,2,0,
Wspro=,,,, 1 ,,,, 0 ,,,, 0 ,,,,-1 ,-1 ,-1 , 0 , 0 , 0 , 0 , 0
BC Design=,, 0 ,, 0 ,,,,,,
BR U #Sta/Elev= 88
  4257.4   44.79  4277.4   44.18  4292.4   43.43  4307.4   43.07  4372.4   42.77
  4402.4   43.12  4417.4   42.96  4472.4   42.94  4482.4   42.71  4497.4   43.27
  4582.4   42.81  4592.4   42.98  4672.4   42.79  4728.5   42.38  4728.6   42.38
  4744.8   42.26  4754.8   40.95  4769.3    42.4  4774.5   42.92  4774.7   42.92
  4823.1   42.25  4823.4   42.62  4823.6   42.86  4864.9   42.94    4866   42.94
  4900.9   42.98  4901.6   42.97  4943.5   42.62  4945.7   42.19  4949.2   41.51
    4962   41.94 4978.69   41.39  4978.8   41.39 4978.91   41.38  4979.1   41.38
 4979.21   41.37  4979.3   41.37  4982.3   41.27    4984   40.58    4990    37.7
  4990.2   37.82  4994.1   35.96  4994.2   35.96  4994.7   35.95  4995.6    32.2
  4999.2   32.15    5005   32.08  5005.3   35.88  5005.8   35.84  5005.9   35.89
  5009.4   37.66    5010   37.68  5016.5   40.63 5018.79   40.95    5019   40.97
 5019.11   40.99 5019.19      41  5019.3   41.02  5019.4   41.03  5022.3   41.43
  5061.7   43.29  5066.6   43.27  5116.8   43.12  5116.9   43.12  5167.8   43.28
  5168.6   43.28  5219.4   43.31    5220    43.3  5234.3   43.05  5258.1   42.63
  5264.3   42.62  5289.3   42.57  5305.4   42.54  5354.2   43.24  5354.3   43.24
  5355.4   43.26  5370.4   42.77  5385.4   43.47  5400.4   43.56  5405.4   43.45
  5420.4   42.55  5435.4   43.13  5800.4   43.47  5815.4   42.92  5825.4    43.4
  5830.4   43.81  5865.4   42.99  5995.4   44.07
BR U #Mann= 5
 4257.40     0.2  4728.5     0.1    4984    0.02  5016.5     0.1  5354.2     0.2
BR U Banks=4984.00,5016.50
BR D #Sta/Elev= 88
  4257.4   44.79  4277.4   44.18  4292.4   43.43  4307.4   43.07  4372.4   42.77
  4402.4   43.12  4417.4   42.96  4472.4   42.94  4482.4   42.71  4497.4   43.27
  4582.4   42.81  4592.4   42.98  4672.4   42.79  4728.5   42.38  4728.6   42.38
  4744.8   42.26  4754.8   40.95  4769.3    42.4  4774.5   42.92  4774.7   42.92
  4823.1   42.25  4823.4   42.62  4823.6   42.86  4864.9   42.94    4866   42.94
  4900.9   42.98  4901.6   42.97  4943.5   42.62  4945.7   42.19  4949.2   41.51
    4962   41.94 4978.69   41.39  4978.8   41.39 4978.91   41.38  4979.1   41.38
 4979.21   41.37  4979.3   41.37  4982.3   41.27    4984   40.58    4990    37.7
  4990.2   37.82  4994.1   35.96  4994.2   35.96  4994.7   35.95  4995.6    32.2
  4999.2   32.15    5005   32.08  5005.3   35.88  5005.8   35.84  5005.9   35.89
  5009.4   37.66    5010   37.68  5016.5   40.63 5018.79   40.95    5019   40.97
 5019.11   40.99 5019.19      41  5019.3   41.02  5019.4   41.03  5022.3   41.43
  5061.7   43.29  5066.6   43.27  5116.8   43.12  5116.9   43.12  5167.8   43.28
  5168.6   43.28  5219.4   43.31    5220    43.3  5234.3   43.05  5258.1   42.63
  5264.3   42.62  5289.3   42.57  5305.4   42.54  5354.2   43.24  5354.3   43.24
  5355.4   43.26  5370.4   42.77  5385.4   43.47  5400.4   43.56  5405.4   43.45
  5420.4   42.55  5435.4   43.13  5800.4   43.47  5815.4   42.92  5825.4    43.4
  5830.4   43.81  5865.4   42.99  5995.4   44.07
BR D #Mann= 5
 4257.40     0.2  4728.5     0.1    4984    0.02  5016.5     0.1  5354.2     0.2
BR D Banks=4984.00,5016.50

Type RM Length L Ch R = 1 ,3744.5,58.3,58.3,58.3
XS GIS Cut Line= 4
      3136557.75     13856214.50      3137010.76     13856403.67
      3137582.27     13856423.71      3138192.53     13856134.73
BEGIN DESCRIPTION:
Downstream Section of Bridge/Culvert/Weir
END DESCRIPTION:
#Sta/Elev= 30
  4257.4   44.78  4307.4   43.06  4728.5   42.37  4744.8   42.25  4754.8   40.94
  4774.5   42.91  4823.1   42.24  4823.6   42.85  4900.9   42.97  4943.5   42.61
  4949.2    41.5    4962   41.93  4982.3   41.26    4984   40.57  4994.7   35.94
  4995.6   32.19    5005   32.07  5005.3   35.87  5016.5   40.62  5061.7   43.28
  5305.4   42.53  5354.2   43.23  5370.4   42.76  5400.4   43.55  5420.4   42.54
  5435.4   43.12  5815.4   42.91  5830.4    43.8  5865.4   42.98  5995.4   44.06
#Mann= 5 , 1 , 0
 4257.40     0.2       0  4728.5     0.1       0    4984    0.02       0
  5016.5     0.1       0  5354.2     0.2       0
#XS Ineff= 2 , 0
       0    4969      42    5030       0      42
Bank Sta=4984.00,5016.50
Exp/Cntr=0.5,0.3

Type RM Length L Ch R = 1 ,3686.2,449.3,452.9,454.8
XS GIS Cut Line= 3
      3136669.09     13856448.56      3137652.26     13856477.91
      3138352.96     13856085.37
BEGIN DESCRIPTION:
Cross Section 3686.2 - Interpolated
END DESCRIPTION:
#Sta/Elev= 30
  4431.6    44.4  4495.2   43.35  4585.2    43.8  4605.2   42.46  4728.5   42.13
  4965.2    41.5  4975.2   40.45    4984    40.5    4990   37.62  4990.2   37.74
  4994.7   35.87  4995.6   32.12    5005      32  5005.3    35.8  5005.9   35.76
  5009.4   37.58    5010    37.6  5016.5   40.55  5025.2   42.43  5045.2   43.13
  5155.2   42.51  5354.2   42.51  5415.2   42.51  5428.4   43.38  5848.4   44.16
  5878.4   43.24  5898.4   43.77  5918.4   43.63  5948.4   44.07  6218.4   44.04
#Mann= 5 , 1 , 0
 4431.60     0.2       0  4728.5     0.1       0    4984    0.02       0
  5016.5     0.1       0  5354.2     0.2       0
Bank Sta=4984.00,5016.50
Exp/Cntr=0.3,0.1

Type RM Length L Ch R = 1 ,3233.3,50.1,49,48.1
XS GIS Cut Line= 4
      3136628.74     13856848.43      3136889.20     13856881.45
      3137505.52     13856914.47      3138008.12     13856492.58
BEGIN DESCRIPTION:
Cross Section 3233.3 - Interpolated
END DESCRIPTION:
#Sta/Elev= 29
  4538.3   43.17  4617.7   42.05  4620.8   42.01  4670.8   42.89  4800.8   43.63
    4948   43.24    4978   41.24  4984.9   40.45  4990.8   37.88  4994.6   34.73
  4995.2   34.74  4996.2   31.48  5000.6   31.48  5004.5   31.48  5004.9   34.73
    5006   34.74  5011.8   37.72    5019   40.46    5028   41.86    5038   42.56
    5298   42.43    5418   43.29  5434.2   43.62  5499.3   43.46  5604.2   43.21
  5644.2      43  5764.2   44.19  5804.2   43.67  6074.2   43.86
#Mann= 5 , 1 , 0
 4538.30     0.2       0  4617.7     0.1       0  4984.9    0.02       0
    5019     0.1       0  5499.3     0.2       0
Bank Sta=4984.90,5019.00
Exp/Cntr=0.5,0.3

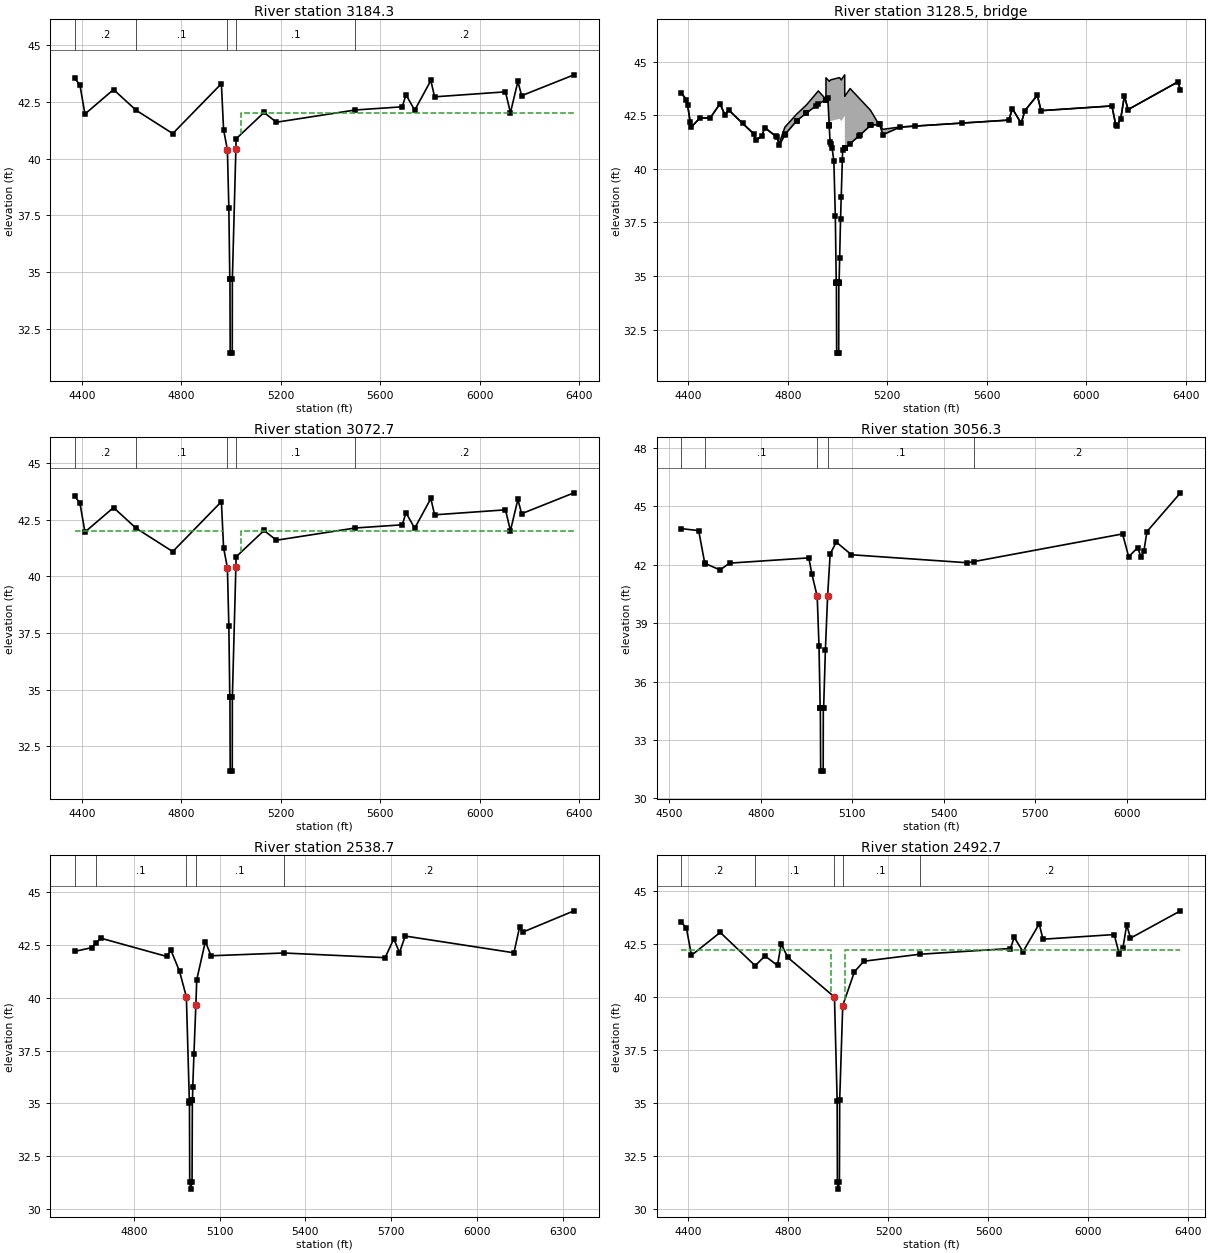
Type RM Length L Ch R = 1 ,3184.3,111.6,111.6,111.6
XS GIS Cut Line= 5
      3136494.02     13856773.49      3136723.43     13856895.76
      3137226.60     13856922.04      3137537.82     13856935.29
      3138228.91     13856311.04
BEGIN DESCRIPTION:
Upstream Section of Bridge/Culvert/Weir
END DESCRIPTION:
#Sta/Elev= 30
  4372.1   43.53  4392.1   43.23  4412.1   41.96  4527.1   43.04  4617.7   42.13
  4765.2    41.1  4960.8    43.3  4969.6   41.27  4984.9   40.39  4990.8   37.82
  4994.6   34.67  4995.2   34.68  4996.2   31.42  5004.5   31.42  5004.9   34.67
    5019    40.4  5020.1   40.87  5132.2   42.03  5182.1    41.6  5499.3   42.14
  5688.1   42.28  5703.1   42.81  5738.1   42.13  5803.1   43.44  5818.1   42.72
  6103.1   42.94  6123.1   42.02  6153.1    43.4  6168.1   42.77  6378.7   43.69
#Mann= 5 , 1 , 0
 4372.10     0.2       0  4617.7     0.1       0  4984.9    0.02       0
    5019     0.1       0  5499.3     0.2       0
#XS Ineff= 2 , 0
       0  4966.4      42    5040       0      42
Bank Sta=4984.90,5019.00
Exp/Cntr=0.5,0.3

Type RM Length L Ch R = 3 ,3128.5,,,
BEGIN DESCRIPTION:
CAVALCADE STREET
Structure ID: H10-11
END DESCRIPTION:
Bridge Culvert--1,0,-1,-1, 0
Deck Dist Width WeirC Skew NumUp NumDn MinLoCord MaxHiCord MaxSubmerge Is_Ogee
10,91.6,2.6,, 53, 53,,,0.95,0,1,1,,
  4372.1  4392.1  4397.1  4407.1  4412.1  4447.1  4487.1  4527.1  4547.1  4562.1
  4662.1  4671.3  4696.3  4706.3  4756.3  4765.2  4787.9  4835.5  4874.9  4922.5
 4953.09  4953.2  4960.8 4966.31  4966.4  4972.9  5008.2  5014.5 5028.49  5028.6
 5028.71 5029.09  5029.2  5050.3  5132.2  5165.7  5168.8  5182.1  5251.2  5688.1
  5703.1  5738.1  5753.1  5803.1  5818.1  6103.1  6118.1  6123.1  6138.1  6153.1
  6168.1  6368.1  6378.7
   43.52   43.22   42.97   42.18   41.95   42.38   42.36   43.03   42.51   42.74
   41.64   41.33   41.54   41.93   41.48   41.18   41.94   42.55   42.98   43.63
   43.24   44.24   44.15   44.08   44.08   44.15   44.25   44.14   44.38   44.38
   43.38   43.39   43.39   43.74   42.73   42.08   42.08   41.84   41.95   42.27
    42.8   42.12   42.71   43.43   42.71   42.93   42.06   42.01   42.31   43.39
   42.76   44.05   43.68
   43.52   43.22   42.97   42.18   41.95   42.38   42.36   43.03   42.51   42.74
   41.63   41.32   41.53   41.92   41.47   41.09   41.58   42.24    42.6   43.01
   43.23   43.23   43.29   42.02   42.16   42.23   42.33   42.22   42.46   42.46
   42.46   42.47   40.95   41.17   42.02   42.07   42.07   41.59   41.94   42.27
    42.8   42.12   42.71   43.43   42.71   42.93   42.06   42.01   42.31   43.39
   42.76   44.05   43.68
  4372.1  4392.1  4397.1  4407.1  4412.1  4447.1  4487.1  4527.1  4547.1  4562.1
  4662.1  4671.3  4696.3  4706.3  4756.3  4765.2  4787.9  4835.5  4874.9  4922.5
 4953.09  4953.2  4960.8 4966.31  4966.4  4972.9  5008.2  5014.5 5028.49  5028.6
 5028.71 5029.09  5029.2  5050.3  5132.2  5165.7  5168.8  5182.1  5251.2  5688.1
  5703.1  5738.1  5753.1  5803.1  5818.1  6103.1  6118.1  6123.1  6138.1  6153.1
  6168.1  6368.1  6378.7
   43.53   43.23   42.98   42.19   41.96   42.39   42.37   43.04   42.52   42.75
   41.64   41.33   41.54   41.93   41.48   41.18   41.94   42.55   42.98   43.63
   43.24   44.24   44.15   44.08   44.08   44.15   44.25   44.14   44.38   44.38
   43.38   43.39   43.39   43.74   42.73   42.08   42.08   41.84   41.95   42.28
   42.81   42.13   42.72   43.44   42.72   42.94   42.07   42.02   42.32    43.4
   42.77   44.06   43.69
   43.53   43.23   42.98   42.19   41.96   42.39   42.37   43.04   42.52   42.75
   41.64   41.33   41.54   41.93   41.48    41.1   41.59   42.25   42.61   43.02
   43.24   43.24    43.3   42.03   42.17   42.24   42.34   42.23   42.47   42.47
   42.47   42.48   40.96   41.18   42.03   42.08   42.08    41.6   41.95   42.28
   42.81   42.13   42.72   43.44   42.72   42.94   42.07   42.02   42.32    43.4
   42.77   44.06   43.69
Abutment Skew #Up #Dn=, 2 , 2
 4966.20 4994.60
   42.16   34.66
 4966.20 4994.60
   42.17   34.67
Abutment Skew #Up #Dn=, 2 , 2
 5006.00 5029.29
   34.72   42.47
 5006.00 5029.29
   34.73   42.48
BR Coef= 1 , 1 , 0 ,1.25, 0 ,,,0.8,0,2,0,
Wspro=,,,, 1 ,,,, 0 ,,,, 0 ,,,,-1 ,-1 ,-1 , 0 , 0 , 0 , 0 , 0
BC Design=,, 0 ,, 0 ,,,,,,
BR U #Sta/Elev= 82
  4372.1   43.52  4392.1   43.22  4397.1   42.97  4407.1   42.18  4412.1   41.95
  4447.1   42.38  4487.1   42.36  4527.1   43.03  4547.1   42.51  4562.1   42.74
  4617.7   42.12  4662.1   41.63  4671.3   41.32  4696.3   41.53  4706.3   41.92
  4750.9   41.52  4756.3   41.47  4765.2   41.09  4787.9   41.58  4789.4   41.61
  4834.9   42.23  4835.5   42.24  4874.7    42.6  4874.9    42.6  4915.1   42.95
  4922.5   43.01 4953.09   43.23  4953.2   43.23 4953.31   43.23  4960.8   43.29
  4966.2   42.04 4966.31   42.02  4966.4      42  4969.6   41.26  4972.9   41.14
  4977.9   40.95  4984.9   40.38  4990.8   37.81  4994.5   34.74  4994.6   34.66
  4995.2   34.67  4996.2   31.41  5000.6   31.41  5004.5   31.41  5004.9   34.66
  5005.9   34.67    5006   34.72  5008.2   35.83  5011.8   37.65  5014.5   38.68
    5019   40.39  5020.1   40.86 5028.49   40.95  5028.6   40.95 5028.71   40.95
 5029.09   40.95  5029.2   40.95  5050.3   41.17  5087.6   41.55  5089.9   41.57
  5132.2   42.02  5134.4   42.02  5165.7   42.07  5168.8   42.07  5182.1   41.59
  5251.2   41.94  5313.1   41.99  5499.3   42.13  5688.1   42.27  5703.1    42.8
  5738.1   42.12  5753.1   42.71  5803.1   43.43  5818.1   42.71  6103.1   42.93
  6118.1   42.06  6123.1   42.01  6138.1   42.31  6153.1   43.39  6168.1   42.76
  6368.1   44.05  6378.7   43.68
BR U #Mann= 5
 4372.10     0.2  4617.7     0.1  4984.9    0.02    5019     0.1  5499.3     0.2
BR U Banks=4984.90,5019.00
BR D #Sta/Elev= 82
  4372.1   43.53  4392.1   43.23  4397.1   42.98  4407.1   42.19  4412.1   41.96
  4447.1   42.39  4487.1   42.37  4527.1   43.04  4547.1   42.52  4562.1   42.75
  4617.7   42.13  4662.1   41.64  4671.3   41.33  4696.3   41.54  4706.3   41.93
  4750.9   41.53  4756.3   41.48  4765.2    41.1  4787.9   41.59  4789.4   41.62
  4834.9   42.24  4835.5   42.25  4874.7   42.61  4874.9   42.61  4915.1   42.96
  4922.5   43.02 4953.09   43.24  4953.2   43.24 4953.31   43.24  4960.8    43.3
  4966.2   42.05 4966.31   42.03  4966.4   42.01  4969.6   41.27  4972.9   41.15
  4977.9   40.96  4984.9   40.39  4990.8   37.82  4994.5   34.75  4994.6   34.67
  4995.2   34.68  4996.2   31.42  5000.6   31.42  5004.5   31.42  5004.9   34.67
  5005.9   34.68    5006   34.73  5008.2   35.84  5011.8   37.66  5014.5   38.69
    5019    40.4  5020.1   40.87 5028.49   40.96  5028.6   40.96 5028.71   40.96
 5029.09   40.96  5029.2   40.96  5050.3   41.18  5087.6   41.56  5089.9   41.58
  5132.2   42.03  5134.4   42.03  5165.7   42.08  5168.8   42.08  5182.1    41.6
  5251.2   41.95  5313.1      42  5499.3   42.14  5688.1   42.28  5703.1   42.81
  5738.1   42.13  5753.1   42.72  5803.1   43.44  5818.1   42.72  6103.1   42.94
  6118.1   42.07  6123.1   42.02  6138.1   42.32  6153.1    43.4  6168.1   42.77
  6368.1   44.06  6378.7   43.69
BR D #Mann= 5
 4372.10     0.2  4617.7     0.1  4984.9    0.02    5019     0.1  5499.3     0.2
BR D Banks=4984.90,5019.00

Type RM Length L Ch R = 1 ,3072.7,16.4,16.4,16.4
XS GIS Cut Line= 5
      3136461.84     13856880.35      3136691.25     13857002.62
      3137194.42     13857028.90      3137505.64     13857042.15
      3138196.73     13856417.90
BEGIN DESCRIPTION:
Downstream Section of Bridge/Culvert/Weir
END DESCRIPTION:
#Sta/Elev= 30
  4372.1   43.52  4392.1   43.22  4412.1   41.95  4527.1   43.03  4617.7   42.12
  4765.2   41.09  4960.8   43.29  4969.6   41.26  4984.9   40.38  4990.8   37.81
  4994.6   34.66  4995.2   34.67  4996.2   31.41  5004.5   31.41  5004.9   34.66
    5019   40.39  5020.1   40.86  5132.2   42.02  5182.1   41.59  5499.3   42.13
  5688.1   42.27  5703.1    42.8  5738.1   42.12  5803.1   43.43  5818.1   42.71
  6103.1   42.93  6123.1   42.01  6153.1   43.39  6168.1   42.76  6378.7   43.68
#Mann= 5 , 1 , 0
 4372.10     0.2       0  4617.7     0.1       0  4984.9    0.02       0
    5019     0.1       0  5499.3     0.2       0
#XS Ineff= 2 , 0
       0  4966.4      42    5040       0      42
Bank Sta=4984.90,5019.00
Exp/Cntr=0.5,0.3

Type RM Length L Ch R = 1 ,3056.3,517.8,517.6,517.5
XS GIS Cut Line= 4
      3136610.39     13857094.23      3136720.45     13857031.86
      3137641.26     13857068.55      3138195.21     13856866.78
BEGIN DESCRIPTION:
Cross Section 3076.3 - Interpolated
END DESCRIPTION:
#Sta/Elev= 30
  4539.4   43.85  4595.9   43.75  4615.9   42.07  4617.7   42.06  4665.9   41.73
  4697.4   42.08  4957.4   42.35  4967.4   41.52  4984.9   40.37  4990.8    37.8
  4994.6   34.65  4995.2   34.66  4996.2    31.4  5004.5    31.4  5004.9   34.65
    5006   34.66  5011.8   37.64    5019   40.38  5027.4   42.55  5047.4   43.16
  5097.4   42.51  5477.4    42.1  5499.3   42.16    5987   43.58    6007   42.41
    6037   42.88    6047   42.39    6057    42.7    6067    43.7    6177   45.69
#Mann= 5 , 1 , 0
 4539.40     0.2       0  4617.7     0.1       0  4984.9    0.02       0
    5019     0.1       0  5499.3     0.2       0
Bank Sta=4984.90,5019.00
Exp/Cntr=0.3,0.1

Type RM Length L Ch R = 1 ,2538.7,47,46,42.9
XS GIS Cut Line= 5
      3136570.04     13857523.45      3136625.07     13857541.79
      3136885.53     13857571.14      3137270.73     13857585.81
      3138224.56     13857174.94
BEGIN DESCRIPTION:
Cross Section 2538.7 - Interpolated
END DESCRIPTION:
#Sta/Elev= 30
  4594.8   42.18  4652.8   42.35    4667   42.55  4684.9    42.8  4914.9   41.94
  4930.4   42.22  4960.4   41.23  4984.1   40.03  4994.7   35.03  4994.9   35.11
  4995.8   31.29  4999.2   30.96    5004    31.3    5005   35.16  5005.5   35.15
  5006.5    35.8  5010.6   37.34  5017.2   39.63  5020.4   40.84  5050.4   42.64
  5070.4   41.97  5325.1    42.1    5679   41.88    5709   42.77    5729   42.12
    5749    42.9    6129   42.11    6149   43.33    6159   43.08    6339   44.09
#Mann= 5 , 1 , 0
 4594.80     0.2       0    4667     0.1       0  4984.1    0.02       0
  5017.2     0.1       0  5325.1     0.2       0
Bank Sta=4984.10,5017.20
Exp/Cntr=0.5,0.3

Type RM Length L Ch R = 1 ,2492.7,51.6,51.6,51.6
XS GIS Cut Line= 6
      3136375.27     13857460.38      3136653.38     13857607.03
      3136862.70     13857615.55      3136979.73     13857619.70
      3137271.43     13857630.36      3138238.55     13857188.94
BEGIN DESCRIPTION:
Upstream Section of Bridge/Culvert/Weir
END DESCRIPTION:
#Sta/Elev= 30
  4372.1   43.53  4392.1   43.23  4412.1   41.96  4527.1   43.04    4667   41.47
  4706.3   41.93  4756.3   41.48  4770.9    42.5  4797.3   41.86  4984.1   39.99
  4994.9   35.07  4995.8   31.25  4999.2   30.92    5004   31.26    5005   35.12
  5017.2   39.59    5064   41.18  5101.4   41.68  5325.1   42.01  5688.1   42.28
  5703.1   42.81  5738.1   42.13  5803.1   43.44  5818.1   42.72  6103.1   42.94
  6123.1   42.02  6138.1   42.32  6153.1    43.4  6168.1   42.77  6368.1   44.06
#Mann= 5 , 1 , 0
 4372.10     0.2       0    4667     0.1       0  4984.1    0.02       0
  5017.2     0.1       0  5325.1     0.2       0
#XS Ineff= 2 , 0
       0    4972    42.2    5025       0    42.2
Bank Sta=4984.10,5017.20
Exp/Cntr=0.5,0.3