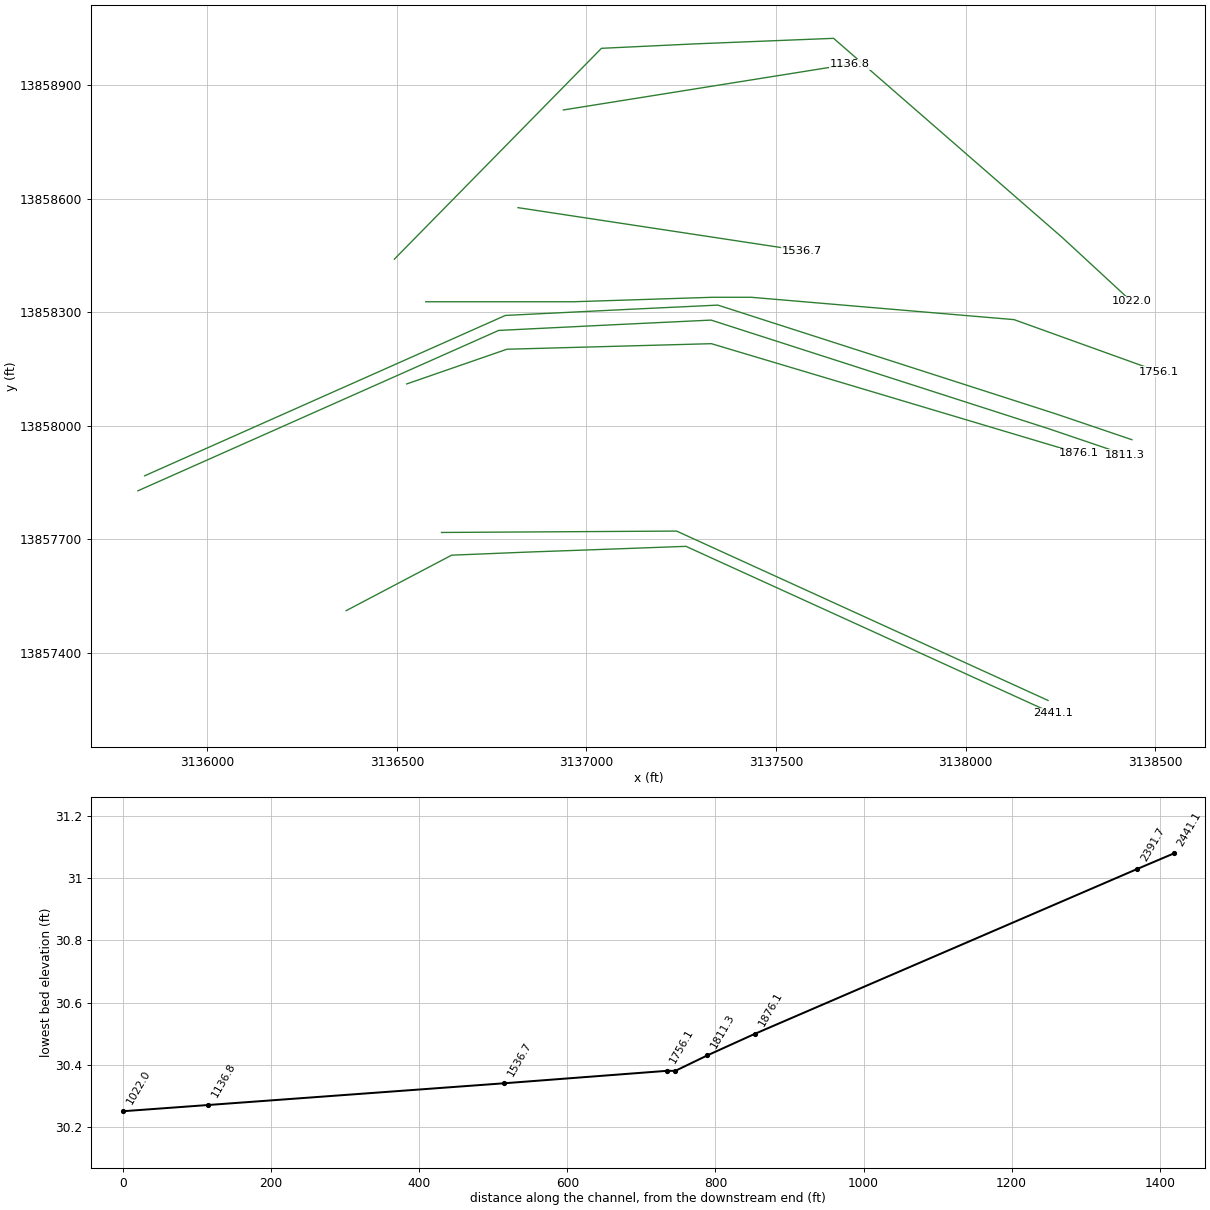
HEC-RAS study H110-00-00.PRJ: H110-00-00

--- H110-00-00.g01 (geometry) --- (continued)

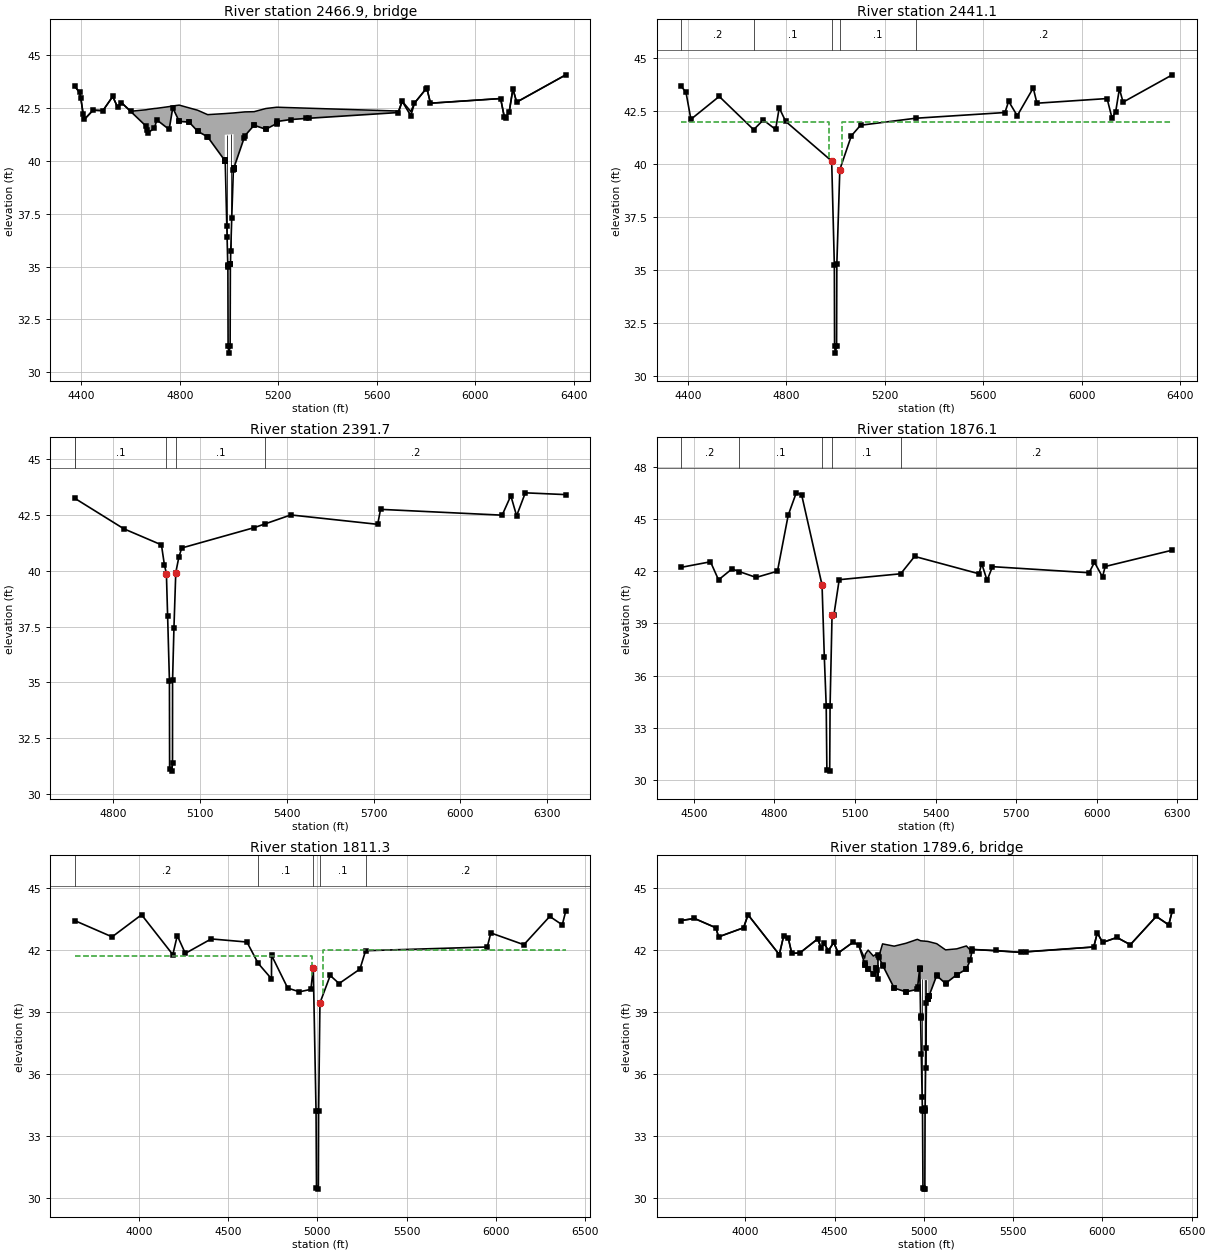
Type RM Length L Ch R = 3 ,2466.9,,,
BEGIN DESCRIPTION:
BUNTE STREET
Structure ID: H10-8
END DESCRIPTION:
Bridge Culvert--1,0,-1,-1, 0
Deck Dist Width WeirC Skew NumUp NumDn MinLoCord MaxHiCord MaxSubmerge Is_Ogee
10,31.6,2.6,, 46, 45,,,0.95,0,1,1,,
  4372.1  4392.1  4397.1  4407.1  4412.1  4447.1  4487.1  4527.1  4547.1  4562.1
    4600  4662.1  4671.3  4696.3  4706.3  4756.3  4770.9  4797.3  4837.2  4871.7
  4912.7  4982.1 4982.21  4982.3 5018.09  5018.2    5064  5101.4  5149.3  5192.9
  5195.3  5196.2  5251.2  5688.1  5703.1  5738.1  5753.1  5803.1  5818.1  6103.1
  6118.1  6123.1  6138.1  6153.1  6168.1  6368.1
   43.52   43.22   42.97   42.18   41.95   42.38   42.36   43.03   42.51   42.74
   42.33    42.4   42.42   42.46   42.47   42.55   42.58   42.62   42.49   42.38
   42.17   42.22   42.22   42.22   42.25   42.25    42.3   42.31   42.46   42.52
   42.52   42.52    42.5   42.34   42.81   42.32   42.72   43.43   42.71   42.93
   42.06   42.01   42.31   43.39   42.76   44.05
   43.52   43.22   42.97   42.18   41.95   42.38   42.36   43.03   42.51   42.74
   42.32   41.63   41.32   41.53   41.92   41.47   42.49   41.85   41.82   41.39
   41.12   40.01   40.01   41.22   41.25   39.61   41.17   41.67   41.48   41.75
   41.77   41.85   41.94   42.27    42.8   42.12   42.71   43.43   42.71   42.93
   42.06   42.01   42.31   43.39   42.76   44.05
  4372.1  4392.1  4397.1  4407.1  4412.1  4447.1  4487.1  4527.1  4547.1  4562.1
    4600  4662.1  4671.3  4696.3  4706.3  4756.3  4770.9  4797.3  4837.2  4871.7
  4911.4 4982.21  4982.3 5018.09  5018.2    5064  5101.4  5149.3  5192.9  5195.3
  5196.2  5251.2  5688.1  5703.1  5738.1  5753.1  5803.1  5818.1  6103.1  6118.1
  6123.1  6138.1  6153.1  6168.1  6368.1
   43.76   43.46   43.21   42.42   42.19   42.62    42.6   43.27   42.75   42.98
   42.56    42.4   42.42   42.46   42.47   42.55   42.73   42.62   42.49   42.38
   42.17   42.22   42.22   42.25   42.25    42.3   42.31   42.46   42.52   42.52
   42.52    42.5   42.51   43.04   42.36   42.95   43.67   42.95   43.17    42.3
   42.25   42.55   43.63      43   44.29
   43.76   43.46   43.21   42.42   42.19   42.62    42.6   43.27   42.75   42.98
   42.56   41.87   41.56   41.77   42.16   41.71   42.73   42.09   42.06   41.63
   41.37   40.25   41.46   41.49   39.85   41.41   41.91   41.72   41.99   42.01
   42.09   42.18   42.51   43.04   42.36   42.95   43.67   42.95   43.17    42.3
   42.25   42.55   43.63      43   44.29
Pier Skew, UpSta & Num, DnSta & Num=,4991.7, 2 ,4991.7, 2 , 0 , 0 , 0 ,,
       1       1
   35.15   42.23
       1       1
   35.39   42.47
Pier Skew, UpSta & Num, DnSta & Num=,5006.5, 2 ,5006.5, 2 , 0 , 0 , 0 ,,
       1       1
   34.43   42.24
       1       1
   34.66   42.48
Abutment Skew #Up #Dn=, 2 , 2
 4982.10 4994.70
   41.22   34.98
 4982.10 4994.70
   41.46   35.22
Abutment Skew #Up #Dn=, 2 , 2
 5005.50 5018.29
   35.10   41.25
 5005.50 5018.29
   35.34   41.49
BR Coef= 1 , 1 , 0 ,1.25, 0 ,,,0.8,0,2,0,
Wspro=,,,, 1 ,,,, 0 ,,,, 0 ,,,,-1 ,-1 ,-1 , 0 , 0 , 0 , 0 , 0
BC Design=,, 0 ,, 0 ,,,,,,
BR U #Sta/Elev= 79
  4372.1   43.52  4392.1   43.22  4397.1   42.97  4407.1   42.18  4412.1   41.95
  4447.1   42.38  4487.1   42.36  4527.1   43.03  4547.1   42.51  4562.1   42.74
    4600   42.32  4662.1   41.63    4667   41.46  4671.3   41.32  4696.3   41.53
  4706.3   41.92  4756.3   41.47  4770.9   42.49  4796.8   41.86  4797.3   41.85
  4835.2   41.82  4837.2   41.82  4871.7   41.39  4872.9   41.38  4911.4   41.13
  4912.7   41.12  4982.1   40.01 4982.21   40.01  4982.3   40.01 4983.29   39.99
  4983.4   39.99 4983.51   39.99  4984.1   39.98  4990.6   36.89  4991.7   36.38
  4994.6   35.03  4994.7   34.98  4994.9   35.06  4995.8   31.24  4999.2   30.91
    5004   31.25    5005   35.11  5005.4    35.1  5005.5    35.1  5006.5   35.75
  5010.6   37.29  5017.2   39.58 5018.09   39.61  5018.2   39.61  5018.3   39.62
 5019.49   39.66  5019.6   39.66 5019.71   39.67    5061   41.07    5064   41.17
  5101.4   41.67  5101.5   41.67  5148.5   41.48  5149.3   41.48  5192.9   41.75
  5195.3   41.77  5196.2   41.85  5251.2   41.94  5313.1   41.99  5325.1      42
  5688.1   42.27  5703.1    42.8  5738.1   42.12  5753.1   42.71  5800.8    43.4
  5803.1   43.43  5818.1   42.71  6103.1   42.93  6118.1   42.06  6123.1   42.01
  6138.1   42.31  6153.1   43.39  6168.1   42.76  6368.1   44.05
BR U #Mann= 5
 4372.10     0.2    4667     0.1  4984.1    0.02  5017.2     0.1  5325.1     0.2
BR U Banks=4984.10,5017.20
BR D #Sta/Elev= 79
  4372.1   43.76  4392.1   43.46  4397.1   43.21  4407.1   42.42  4412.1   42.19
  4447.1   42.62  4487.1    42.6  4527.1   43.27  4547.1   42.75  4562.1   42.98
    4600   42.56  4662.1   41.87    4667    41.7  4671.3   41.56  4696.3   41.77
  4706.3   42.16  4756.3   41.71  4770.9   42.73  4796.8    42.1  4797.3   42.09
  4835.2   42.06  4837.2   42.06  4871.7   41.63  4872.9   41.62  4911.4   41.37
  4912.7   41.36  4982.1   40.25 4982.21   40.25  4982.3   40.25 4983.29   40.23
  4983.4   40.23 4983.51   40.23  4984.1   40.22  4990.6   37.13  4991.7   36.62
  4994.6   35.27  4994.7   35.22  4994.9    35.3  4995.8   31.48  4999.2   31.15
    5004   31.49    5005   35.35  5005.4   35.34  5005.5   35.34  5006.5   35.99
  5010.6   37.53  5017.2   39.82 5018.09   39.85  5018.2   39.85  5018.3   39.86
 5019.49    39.9  5019.6    39.9 5019.71   39.91    5061   41.31    5064   41.41
  5101.4   41.91  5101.5   41.91  5148.5   41.72  5149.3   41.72  5192.9   41.99
  5195.3   42.01  5196.2   42.09  5251.2   42.18  5313.1   42.23  5325.1   42.24
  5688.1   42.51  5703.1   43.04  5738.1   42.36  5753.1   42.95  5800.8   43.64
  5803.1   43.67  5818.1   42.95  6103.1   43.17  6118.1    42.3  6123.1   42.25
  6138.1   42.55  6153.1   43.63  6168.1      43  6368.1   44.29
BR D #Mann= 5
 4372.10     0.2    4667     0.1  4984.1    0.02  5017.2     0.1  5325.1     0.2
BR D Banks=4984.10,5017.20

Type RM Length L Ch R = 1 ,2441.1,49.4,49.4,49.4
XS GIS Cut Line= 6
      3136366.29     13857511.19      3136644.40     13857657.85
      3136853.72     13857666.37      3136970.75     13857670.52
      3137262.45     13857681.18      3138229.58     13857239.75
BEGIN DESCRIPTION:
Downstream Section of Bridge/Culvert/Weir
END DESCRIPTION:
#Sta/Elev= 30
  4372.1   43.69  4392.1   43.39  4412.1   42.12  4527.1    43.2    4667   41.63
  4706.3   42.09  4756.3   41.64  4770.9   42.66  4797.3   42.02  4984.1   40.15
  4994.9   35.23  4995.8   31.41  4999.2   31.08    5004   31.42    5005   35.28
  5017.2   39.75    5064   41.34  5101.4   41.84  5325.1   42.17  5688.1   42.44
  5703.1   42.97  5738.1   42.29  5803.1    43.6  5818.1   42.88  6103.1    43.1
  6123.1   42.18  6138.1   42.48  6153.1   43.56  6168.1   42.93  6368.1   44.22
#Mann= 5 , 1 , 0
 4372.10     0.2       0    4667     0.1       0  4984.1    0.02       0
  5017.2     0.1       0  5325.1     0.2       0
#XS Ineff= 2 , 0
       0    4972      42    5025       0      42
Bank Sta=4984.10,5017.20
Exp/Cntr=0.5,0.3

Type RM Length L Ch R = 1 ,2391.7,508.9,515.6,516.8
XS GIS Cut Line= 3
      3136617.73     13857717.88      3137237.72     13857721.55
      3138217.22     13857273.99
BEGIN DESCRIPTION:
Cross Section 2391.7 - Interpolated
END DESCRIPTION:
#Sta/Elev= 25
    4667   43.25    4837   41.88    4967   41.16    4977   40.28 4984.09   39.87
 4988.29   37.99 4994.59   35.07 4995.19   31.12 5002.79   31.03 5005.19   31.38
 5005.39    35.1 5010.19   37.45 5016.49   39.92    5027    40.6    5037   41.02
    5287   41.93  5325.1    42.1  5413.9    42.5  5713.9   42.08  5723.9   42.75
  6143.9   42.49  6173.9   43.36  6193.9   42.46  6223.9   43.49  6363.9   43.41
#Mann= 5 , 1 , 0
 4667.00     0.2       0    4667     0.1       0 4984.09    0.02       0
 5016.49     0.1       0  5325.1     0.2       0
Bank Sta=4984.09,5016.49
Exp/Cntr=0.3,0.1

Type RM Length L Ch R = 1 ,1876.1,61.7,64.8,65
XS GIS Cut Line= 4
      3136526.02     13858110.42      3136790.15     13858202.13
      3137329.43     13858216.81      3138297.93     13857926.99
BEGIN DESCRIPTION:
Cross Section 1876.1 - Interpolated
END DESCRIPTION:
#Sta/Elev= 30
  4452.1   42.23  4561.7   42.55  4591.7   41.51  4641.7   42.14  4668.5   41.99
  4731.7   41.65  4811.2   42.01  4851.2   45.23  4881.2   46.52  4901.2   46.41
  4977.3   41.21  4985.8   37.05  4992.8   34.26  4995.3   30.57  5005.8    30.5
  5007.2   34.27  5014.6   39.51  5021.2   39.47  5041.2   41.52  5270.3   41.86
  5322.1   42.86  5562.1   41.86  5572.1   42.45  5592.1   41.48  5612.1   42.27
  5972.1   41.92  5992.1   42.52  6022.1   41.68  6032.1   42.28  6282.1   43.22
#Mann= 5 , 1 , 0
 4452.10     0.2       0  4668.5     0.1       0  4977.3    0.02       0
  5014.6     0.1       0  5270.3     0.2       0
Bank Sta=4977.30,5014.60
Exp/Cntr=0.5,0.3

Type RM Length L Ch R = 1 ,1811.3,43.4,43.4,43.4
XS GIS Cut Line= 6
      3135817.06     13857827.99      3136768.43     13858251.83
      3137083.50     13858267.42      3137328.72     13858279.15
      3138219.91     13857991.76      3138420.66     13857923.47
BEGIN DESCRIPTION:
Upstream Section of Bridge/Culvert/Weir
END DESCRIPTION:
#Sta/Elev= 30
  3640.7   43.43  3850.7   42.64  4015.7   43.71  4190.7   41.78  4215.7    42.7
  4260.7   41.84  4405.7   42.54  4605.7   42.39  4668.5   41.36  4743.3   40.61
  4743.5   41.75  4834.1   40.16    4900   39.98  4963.9    40.1  4977.3   41.14
  4992.8   34.19  4995.3    30.5  5005.8   30.43  5007.2    34.2  5014.6   39.44
  5072.2   40.77  5121.8   40.38  5238.5   41.08  5270.3   41.97  5951.6   42.15
  5971.6   42.83  6156.6   42.26  6301.6   43.63  6371.6   43.22  6391.6    43.9
#Mann= 5 , 1 , 0
 3640.70     0.2       0  4668.5     0.1       0  4977.3    0.02       0
  5014.6     0.1       0  5270.3     0.2       0
#XS Ineff= 2 , 0
       0    4972    41.7    5033       0      42
Bank Sta=4977.30,5014.60
Exp/Cntr=0.5,0.3

Type RM Length L Ch R = 3 ,1789.6,,,
BEGIN DESCRIPTION:
BRIDGE RAND STREET
Structure ID: H10-6
END DESCRIPTION:
Bridge Culvert--1,0,-1,-1, 0
Deck Dist Width WeirC Skew NumUp NumDn MinLoCord MaxHiCord MaxSubmerge Is_Ogee
10,23.4,2.6,, 55, 55,,,0.95,0,1,1,,
  3640.7  3715.7  3835.7  3850.7  3990.7  4015.7  4190.7  4215.7  4240.7  4260.7
  4305.7  4405.7  4425.7  4440.7  4465.7  4495.7  4520.7  4605.7  4635.7  4668.5
  4672.6  4688.3  4717.6  4723.3  4733.3  4738.3  4743.3  4743.5  4747.6    4769
  4834.1    4900  4963.9  4977.3 4982.21  4982.3 5022.19  5022.3  5022.4  5072.2
  5121.8  5184.4  5238.5  5260.1  5270.3  5271.6  5541.6  5951.6  5971.6  6001.6
  6081.6  6156.6  6301.6  6371.6  6391.6
   43.42   43.52   43.07   42.63   43.07    43.7   41.77   42.69   42.58   41.83
   41.85   42.53   42.08   42.33   41.96   42.36   41.85   42.38   42.22    41.6
    41.8   41.99    41.7   41.74   41.78   41.65   41.51   41.74   41.66   42.29
   42.18   42.32   42.51   42.46   42.44   42.44   42.41   42.41   42.41    42.3
      42   42.05   42.19   41.99   41.96   42.02   41.88   42.14   42.82   42.36
    42.6   42.25   43.62   43.21   43.89
   43.42   43.52   43.07   42.63   43.07    43.7   41.77   42.69   42.58   41.83
   41.85   42.53   42.08   42.33   41.96   42.36   41.85   42.38   42.22   41.35
   41.27   41.06   40.85   40.81   41.14   41.02    40.6   41.74   41.66   41.27
   40.15   39.97   40.09   41.13   38.73   40.58   40.55   39.61   39.61   40.76
   40.37   40.79   41.07    41.5   41.96   42.02   41.88   42.14   42.82   42.36
    42.6   42.25   43.62   43.21   43.89
  3640.7  3715.7  3835.7  3850.7  3990.7  4015.7  4190.7  4215.7  4240.7  4260.7
  4305.7  4405.7  4425.7  4440.7  4465.7  4495.7  4520.7  4605.7  4635.7  4668.5
  4672.6  4688.3  4717.6  4723.3  4733.3  4738.3  4743.3  4743.5  4747.6    4769
  4834.1    4900  4963.9  4977.3 4982.21  4982.3 5022.19  5022.3  5022.4  5072.2
  5121.8  5184.4  5238.5  5260.1  5270.3  5271.6  5541.6  5951.6  5971.6  6001.6
  6081.6  6156.6  6301.6  6371.6  6391.6
   43.38   43.48   43.03   42.59   43.03   43.66   41.73   42.65   42.54   41.79
   41.81   42.49   42.04   42.29   41.92   42.32   41.81   42.34   42.18    41.6
    41.8   41.99    41.7   41.74   41.78   41.65   41.51   41.71   41.63   42.29
   42.18   42.32   42.51   42.46   42.44   42.44   42.41   42.41   42.41    42.3
      42   42.05   42.19   41.99   41.93   41.98   41.84    42.1   42.78   42.32
   42.56   42.21   43.58   43.17   43.85
   43.34   43.44   42.99   42.55   42.99   43.62   41.69   42.61    42.5   41.75
   41.77   42.45      42   42.25   41.88   42.28   41.77    42.3   42.14   41.27
   41.19   40.98   40.77   40.73   41.06   40.94   40.52   41.66   41.58   41.19
   40.07   39.89   40.01   41.05   38.65    40.5   40.47   39.53   39.53   40.68
   40.29   40.71   40.99   41.42   41.88   41.94    41.8   42.06   42.74   42.28
   42.52   42.17   43.54   43.13   43.81
Pier Skew, UpSta & Num, DnSta & Num=,4990.7, 2 ,4990.7, 2 , 0 , 0 , 0 ,,
       1       1
   33.66   41.57
       1       1
   33.58   41.49
Pier Skew, UpSta & Num, DnSta & Num=,5010.0, 2 ,5010.0, 2 , 0 , 0 , 0 ,,
       1       1
   34.87   41.56
       1       1
   34.79   41.48
Abutment Skew #Up #Dn=, 2 , 2
 4982.10 4992.20
   40.58   34.24
 4982.10 4992.20
   40.50   34.16
Abutment Skew #Up #Dn=, 2 , 2
 5007.60 5022.39
   34.35   40.55
 5007.60 5022.39
   34.27   40.47
BR Coef= 1 , 1 , 0 ,1.25, 0 ,,,0.8,0,2,0,
Wspro=,,,, 1 ,,,, 0 ,,,, 0 ,,,,-1 ,-1 ,-1 , 0 , 0 , 0 , 0 , 0
BC Design=,, 0 ,, 0 ,,,,,,
BR U #Sta/Elev= 89
  3640.7   43.42  3715.7   43.52  3835.7   43.07  3850.7   42.63  3990.7   43.07
  4015.7    43.7  4190.7   41.77  4215.7   42.69  4240.7   42.58  4260.7   41.83
  4305.7   41.85  4405.7   42.53  4425.7   42.08  4440.7   42.33  4465.7   41.96
  4495.7   42.36  4520.7   41.85  4605.7   42.38  4635.7   42.22  4668.5   41.35
  4670.7   41.29  4672.6   41.27  4687.6   41.07  4688.3   41.06  4717.6   40.85
  4723.3   40.81  4732.6   41.12  4733.3   41.14  4738.3   41.02  4743.3    40.6
  4743.5   41.74  4747.6   41.66    4769   41.27  4770.4   41.24  4833.6   40.16
  4834.1   40.15    4900   39.97  4901.3   39.97  4963.9   40.09  4965.2   40.19
 4976.39   41.06  4976.5   41.07 4976.61   41.08  4977.3   41.13  4982.1   38.78
 4982.21   38.73  4982.3   38.68  4985.8   36.97  4990.7   34.87  4992.1   34.28
  4992.2   34.24  4992.8   34.18  4995.3   30.49  5000.5   30.45  5005.8   30.42
  5007.2   34.19  5007.5   34.27  5007.6   34.35    5010   36.27  5011.7   37.27
  5014.6   39.43 5022.19   39.61  5022.3   39.61  5022.4   39.61 5028.99   39.76
  5029.1   39.76 5029.21   39.77  5072.2   40.76    5073   40.75  5121.8   40.37
  5122.8   40.38  5183.7   40.79  5184.4   40.79  5238.4   41.07  5238.5   41.07
  5260.1    41.5  5270.3   41.96  5271.6   42.02  5401.6   41.97  5541.6   41.88
  5571.6   41.91  5951.6   42.14  5971.6   42.82  6001.6   42.36  6081.6    42.6
  6156.6   42.25  6301.6   43.62  6371.6   43.21  6391.6   43.89
BR U #Mann= 5
 3640.70     0.2  4668.5     0.1  4977.3    0.02  5014.6     0.1  5270.3     0.2
BR U Banks=4977.30,5014.60
BR D #Sta/Elev= 89
  3640.7   43.34  3715.7   43.44  3835.7   42.99  3850.7   42.55  3990.7   42.99
  4015.7   43.62  4190.7   41.69  4215.7   42.61  4240.7    42.5  4260.7   41.75
  4305.7   41.77  4405.7   42.45  4425.7      42  4440.7   42.25  4465.7   41.88
  4495.7   42.28  4520.7   41.77  4605.7    42.3  4635.7   42.14  4668.5   41.27
  4670.7   41.21  4672.6   41.19  4687.6   40.99  4688.3   40.98  4717.6   40.77
  4723.3   40.73  4732.6   41.04  4733.3   41.06  4738.3   40.94  4743.3   40.52
  4743.5   41.66  4747.6   41.58    4769   41.19  4770.4   41.16  4833.6   40.08
  4834.1   40.07    4900   39.89  4901.3   39.89  4963.9   40.01  4965.2   40.11
 4976.39   40.98  4976.5   40.99 4976.61      41  4977.3   41.05  4982.1    38.7
 4982.21   38.65  4982.3    38.6  4985.8   36.89  4990.7   34.79  4992.1    34.2
  4992.2   34.16  4992.8    34.1  4995.3   30.41  5000.5   30.37  5005.8   30.34
  5007.2   34.11  5007.5   34.19  5007.6   34.27    5010   36.19  5011.7   37.19
  5014.6   39.35 5022.19   39.53  5022.3   39.53  5022.4   39.53 5028.99   39.68
  5029.1   39.68 5029.21   39.69  5072.2   40.68    5073   40.67  5121.8   40.29
  5122.8    40.3  5183.7   40.71  5184.4   40.71  5238.4   40.99  5238.5   40.99
  5260.1   41.42  5270.3   41.88  5271.6   41.94  5401.6   41.89  5541.6    41.8
  5571.6   41.83  5951.6   42.06  5971.6   42.74  6001.6   42.28  6081.6   42.52
  6156.6   42.17  6301.6   43.54  6371.6   43.13  6391.6   43.81
BR D #Mann= 5
 3640.70     0.2  4668.5     0.1  4977.3    0.02  5014.6     0.1  5270.3     0.2
BR D Banks=4977.30,5014.60

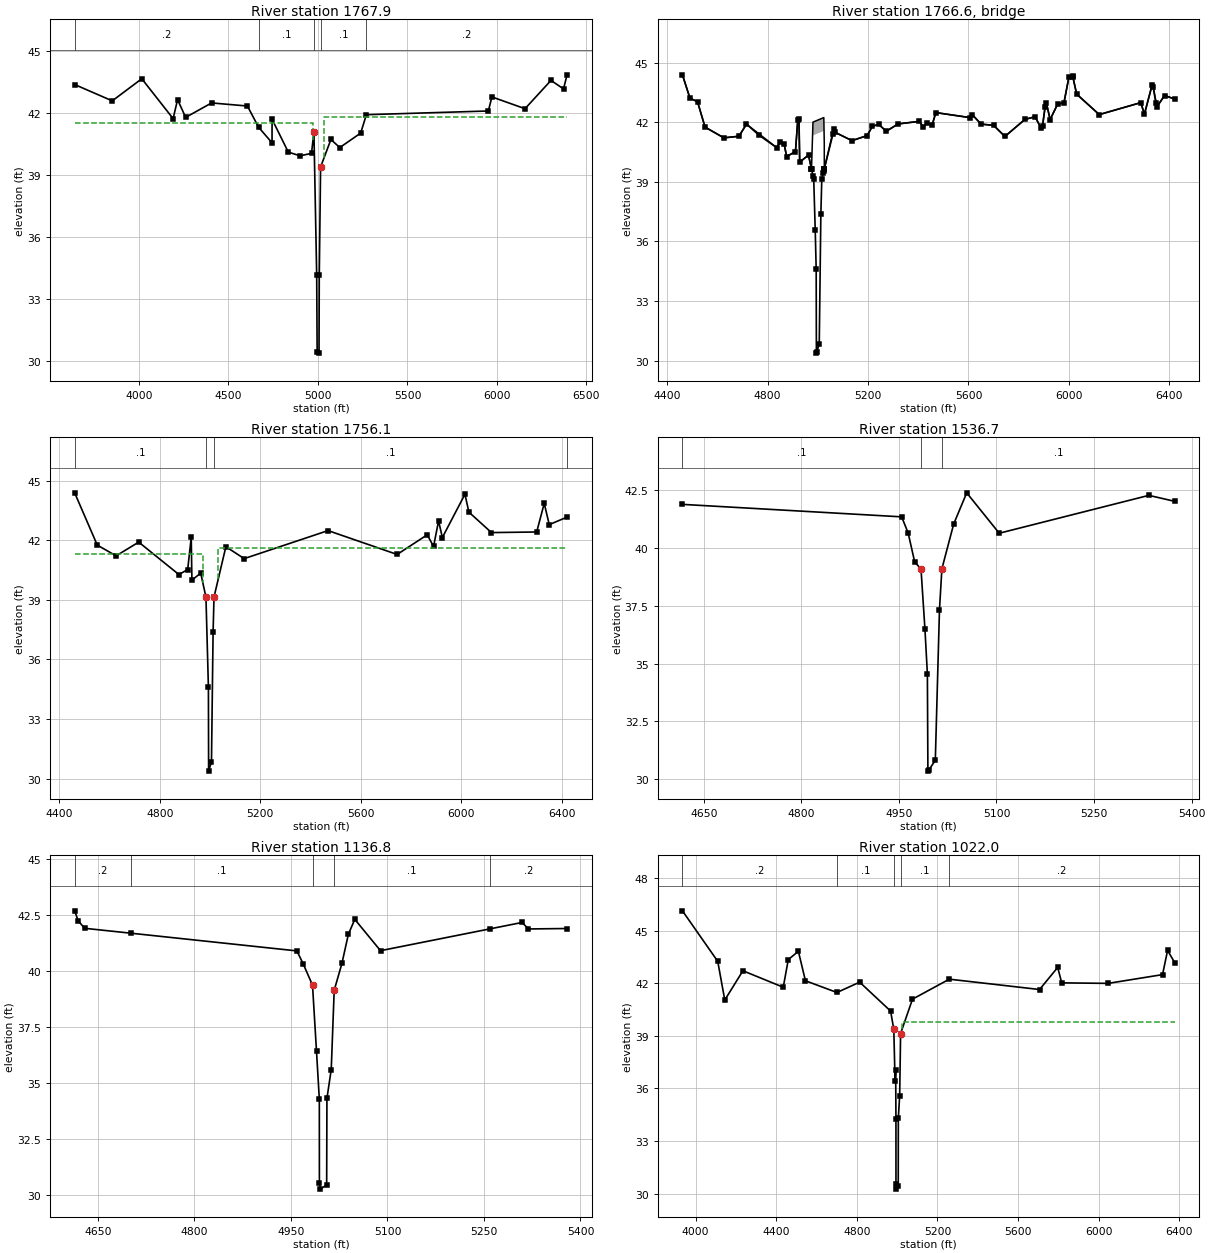
Type RM Length L Ch R = 1 ,1767.9,11.8,11.8,11.8
XS GIS Cut Line= 6
      3135834.78     13857867.61      3136786.15     13858291.45
      3137101.22     13858307.04      3137346.44     13858318.77
      3138237.63     13858031.38      3138438.38     13857963.09
BEGIN DESCRIPTION:
Downstream Section of Bridge/Culvert/Weir
END DESCRIPTION:
#Sta/Elev= 30
  3640.7   43.38  3850.7   42.59  4015.7   43.66  4190.7   41.73  4215.7   42.65
  4260.7   41.79  4405.7   42.49  4605.7   42.34  4668.5   41.31  4743.3   40.56
  4743.5    41.7  4834.1   40.11    4900   39.93  4963.9   40.05  4977.3   41.09
  4992.8   34.14  4995.3   30.45  5005.8   30.38  5007.2   34.15  5014.6   39.39
  5072.2   40.72  5121.8   40.33  5238.5   41.03  5270.3   41.92  5951.6    42.1
  5971.6   42.78  6156.6   42.21  6301.6   43.58  6371.6   43.17  6391.6   43.85
#Mann= 5 , 1 , 0
 3640.70     0.2       0  4668.5     0.1       0  4977.3    0.02       0
  5014.6     0.1       0  5270.3     0.2       0
#XS Ineff= 2 , 0
       0    4972    41.5    5033       0    41.8
Bank Sta=4977.30,5014.60
Exp/Cntr=0.5,0.3

Type RM Length L Ch R = 3 ,1766.6,,,
BEGIN DESCRIPTION:
Pipeline
END DESCRIPTION:
Bridge Culvert--1,0,-1,-1, 0
Deck Dist Width WeirC Skew NumUp NumDn MinLoCord MaxHiCord MaxSubmerge Is_Ogee
10,1,2.6,, 60, 60,,,0.95,0,1,1,,
  4461.3  4491.3  4521.3  4551.3  4626.3  4686.3  4716.3  4836.3  4851.2  4866.2
  4876.2  4911.2 4920.45 4925.35 4928.05 4963.15 4975.15 4980.95 5024.15 5025.84
 5025.95 5026.05 5063.25 5066.95  5136.2  5196.2  5217.6  5242.6  5272.6    5320
    5405    5420    5435    5455    5470    5605    5615    5650    5700    5745
    5825    5865    5890    5895    5905    5910    5925    5955    5980    6000
    6015  6030.6  6120.6  6285.6  6300.6  6330.6  6335.6  6350.6  6380.6  6421.6
   44.38    43.2   43.03   41.75   41.21   41.29    41.9   40.72   41.01   40.89
   40.27   40.52   42.11   42.14   39.99   40.34   39.65      42   42.23   41.01
   40.93   39.65   41.67    41.5   41.07   41.32   41.79   41.89   41.54   41.91
   42.04   41.74   41.96   41.84   42.48   42.23   42.38    41.9   41.84   41.28
   42.14   42.27   41.68   41.83   42.76   42.97   42.13   42.91   42.97   44.28
   44.31   43.41   42.38   42.98   42.41   43.85   43.75   42.78   43.34   43.16
   44.38    43.2   43.03   41.75   41.21   41.29    41.9   40.72   41.01   40.89
   40.27   40.52   42.11   42.14   39.99   40.34   39.64   41.33   41.56   40.34
   39.65   39.65   41.67    41.5   41.07   41.32   41.79   41.89   41.54   41.91
   42.04   41.74   41.96   41.84   42.48   42.23   42.38    41.9   41.84   41.28
   42.14   42.27   41.68   41.83   42.76   42.97   42.13   42.91   42.97   44.28
   44.31   43.41   42.38   42.98   42.41   43.85   43.75   42.78   43.34   43.16
  4461.3  4491.3  4521.3  4551.3  4626.3  4686.3  4716.3  4836.3  4851.2  4866.2
  4876.2  4911.2 4920.45 4925.35 4928.05 4963.15 4975.15 4980.95 5024.15 5025.84
 5025.95 5026.05 5063.25 5066.95  5136.2  5196.2  5217.6  5242.6  5272.6    5320
    5405    5420    5435    5455    5470    5605    5615    5650    5700    5745
    5825    5865    5890    5895    5905    5910    5925    5955    5980    6000
    6015  6030.6  6120.6  6285.6  6300.6  6330.6  6335.6  6350.6  6380.6  6421.6
   44.38    43.2   43.03   41.75   41.21   41.29    41.9   40.72   41.01   40.89
   40.27   40.52   42.11   42.14   39.99   40.34   39.65      42   42.23   41.01
   40.93   39.65   41.67    41.5   41.07   41.32   41.79   41.89   41.54   41.91
   42.04   41.74   41.96   41.84   42.48   42.23   42.38    41.9   41.84   41.28
   42.14   42.27   41.68   41.83   42.76   42.97   42.13   42.91   42.97   44.28
   44.31   43.41   42.38   42.98   42.41   43.85   43.75   42.78   43.34   43.16
   44.38    43.2   43.03   41.75   41.21   41.29    41.9   40.72   41.01   40.89
   40.27   40.52   42.11   42.14   39.99   40.34   39.64   41.33   41.56   40.34
   39.65   39.65   41.67    41.5   41.07   41.32   41.79   41.89   41.54   41.91
   42.04   41.74   41.96   41.84   42.48   42.23   42.38    41.9   41.84   41.28
   42.14   42.27   41.68   41.83   42.76   42.97   42.13   42.91   42.97   44.28
   44.31   43.41   42.38   42.98   42.41   43.85   43.75   42.78   43.34   43.16
BR Coef= 1 , 1 , 0 ,1.25, 0 ,,,0.8,0,2,0,
Wspro=,,,, 1 ,,,, 0 ,,,, 0 ,,,,-1 ,-1 ,-1 , 0 , 0 , 0 , 0 , 0
BC Design=,, 0 ,, 0 ,,,,,,
BR U #Sta/Elev= 75
  4461.3   44.38  4491.3    43.2  4521.3   43.03  4551.3   41.75  4626.3   41.21
  4686.3   41.29  4716.3    41.9  4766.3   41.34  4836.3   40.72  4851.2   41.01
  4866.2   40.89  4876.2   40.27  4911.2   40.52 4920.45   42.11 4925.35   42.14
 4928.05   39.99 4963.15   40.34 4974.95   39.65 4975.06   39.65 4975.15   39.64
 4980.95    39.3 4983.95   39.13 4989.95   36.55 4993.75   34.59 4994.55   30.38
 4995.85   30.42 5005.95   30.85 5012.35   37.37 5016.05   39.14 5021.85   39.44
 5024.15   39.56 5025.84   39.64 5025.95   39.65 5026.05   39.65 5060.05   41.38
 5063.25   41.67 5066.95    41.5  5136.2   41.07  5196.2   41.32  5217.6   41.79
  5242.6   41.89  5272.6   41.54    5320   41.91    5405   42.04    5420   41.74
    5435   41.96    5455   41.84    5470   42.48    5605   42.23    5615   42.38
    5650    41.9    5700   41.84    5745   41.28    5825   42.14    5865   42.27
    5890   41.68    5895   41.83    5905   42.76    5910   42.97    5925   42.13
    5955   42.91    5980   42.97    6000   44.28    6015   44.31  6015.6   44.27
  6030.6   43.41  6120.6   42.38  6285.6   42.98  6300.6   42.41  6330.6   43.85
  6335.6   43.75  6345.6   42.97  6350.6   42.78  6380.6   43.34  6421.6   43.16
BR U #Mann= 4
 4461.30     0.1 4983.95    0.02 5016.05     0.1  6421.6     0.2
BR U Banks=4983.95,5016.05
BR D #Sta/Elev= 75
  4461.3   44.38  4491.3    43.2  4521.3   43.03  4551.3   41.75  4626.3   41.21
  4686.3   41.29  4716.3    41.9  4766.3   41.34  4836.3   40.72  4851.2   41.01
  4866.2   40.89  4876.2   40.27  4911.2   40.52 4920.45   42.11 4925.35   42.14
 4928.05   39.99 4963.15   40.34 4974.95   39.65 4975.06   39.65 4975.15   39.64
 4980.95    39.3 4983.95   39.13 4989.95   36.55 4993.75   34.59 4994.55   30.38
 4995.85   30.42 5005.95   30.85 5012.35   37.37 5016.05   39.14 5021.85   39.44
 5024.15   39.56 5025.84   39.64 5025.95   39.65 5026.05   39.65 5060.05   41.38
 5063.25   41.67 5066.95    41.5  5136.2   41.07  5196.2   41.32  5217.6   41.79
  5242.6   41.89  5272.6   41.54    5320   41.91    5405   42.04    5420   41.74
    5435   41.96    5455   41.84    5470   42.48    5605   42.23    5615   42.38
    5650    41.9    5700   41.84    5745   41.28    5825   42.14    5865   42.27
    5890   41.68    5895   41.83    5905   42.76    5910   42.97    5925   42.13
    5955   42.91    5980   42.97    6000   44.28    6015   44.31  6015.6   44.27
  6030.6   43.41  6120.6   42.38  6285.6   42.98  6300.6   42.41  6330.6   43.85
  6335.6   43.75  6345.6   42.97  6350.6   42.78  6380.6   43.34  6421.6   43.16
BR D #Mann= 4
 4461.30     0.1 4983.95    0.02 5016.05     0.1  6421.6     0.2
BR D Banks=4983.95,5016.05

Type RM Length L Ch R = 1 ,1756.1,219.4,219.4,219.4
XS GIS Cut Line= 6
      3136576.23     13858327.63      3136966.06     13858327.63
      3137332.29     13858339.44      3137434.68     13858339.44
      3138127.76     13858280.37      3138509.74     13858142.54
BEGIN DESCRIPTION:
Downstream Section of Bridge/Culvert/Weir
END DESCRIPTION:
#Sta/Elev= 30
  4461.3   44.38  4551.3   41.75  4626.3   41.21  4716.3    41.9  4876.2   40.27
  4911.2   40.52 4925.35   42.14 4928.05   39.99 4963.15   40.34 4983.95   39.13
 4993.75   34.59 4994.55   30.38 5005.95   30.85 5012.35   37.37 5016.05   39.14
 5063.25   41.67  5136.2   41.07    5470   42.48    5745   41.28    5865   42.27
    5890   41.68    5910   42.97    5925   42.13    6015   44.31  6030.6   43.41
  6120.6   42.38  6300.6   42.41  6330.6   43.85  6350.6   42.78  6421.6   43.16
#Mann= 4 , 1 , 0
 4461.30     0.1       0 4983.95    0.02       0 5016.05     0.1       0
  6421.6     0.2       0
#XS Ineff= 2 , 0
       0    4972    41.3    5033       0    41.6
Bank Sta=4983.95,5016.05
Exp/Cntr=0.5,0.3

Type RM Length L Ch R = 1 ,1536.7,379.9,399.9,412.2
XS GIS Cut Line= 2
      3136819.50     13858576.33      3137567.89     13858462.60
BEGIN DESCRIPTION:
Cross Section 1536.7 - Interpolated
END DESCRIPTION:
#Sta/Elev= 17
  4617.2   41.89  4954.2   41.35  4964.2   40.65  4974.2    39.4 4983.95   39.09
 4989.95   36.51 4993.75   34.55 4994.55   30.34 4995.85   30.38 5005.95   30.81
 5012.35   37.33 5016.05    39.1  5034.2   41.04  5054.2   42.39  5104.2   40.64
  5334.2   42.28  5374.2   42.02
#Mann= 3 , 1 , 0
 4617.20     0.1       0 4983.95    0.02       0 5016.05     0.1       0
Bank Sta=4983.95,5016.05
Exp/Cntr=0.3,0.1

Type RM Length L Ch R = 1 ,1136.8,115,114.8,105.9
XS GIS Cut Line= 2
      3136939.20     13858834.53      3137694.97     13858955.60
BEGIN DESCRIPTION:
Cross Section 1136.8 - Interpolated
END DESCRIPTION:
#Sta/Elev= 23
  4613.8    42.7  4619.2   42.26  4629.2   41.92  4701.5    41.7  4959.2   40.91
  4969.2   40.32  4983.5   39.38  4989.7   36.43  4994.1   34.28  4994.2   30.54
  4995.8   30.27  5005.5   30.46  5005.9   34.32  5012.6   35.61  5017.2   39.15
  5029.2   40.35  5039.2   41.65  5049.2   42.32  5089.2   40.92  5258.6   41.89
  5309.2   42.18  5319.2   41.89  5379.2   41.91
#Mann= 5 , 1 , 0
 4613.80     0.2       0  4701.5     0.1       0  4983.5    0.02       0
  5017.2     0.1       0  5258.6     0.2       0
Bank Sta=4983.50,5017.20
Exp/Cntr=0.5,0.3

Type RM Length L Ch R = 1 ,1022.0,24,24,24
XS GIS Cut Line= 6
      3136493.40     13858440.23      3137039.56     13858997.42
      3137285.81     13859009.15      3137651.74     13859023.81
      3138254.76     13858497.49      3138437.34     13858328.44
BEGIN DESCRIPTION:
Upstream Section of Bridge/Culvert/Weir
END DESCRIPTION:
#Sta/Elev= 30
  3935.2   46.13  4110.2   43.25  4145.2   41.04  4235.2   42.71  4435.2   41.77
  4460.2   43.35  4510.2   43.82  4545.2   42.14  4701.5   41.47  4814.2   42.06
  4967.7   40.41  4983.5   39.36  4989.7   36.41  4992.7   37.02  4994.1   34.26
  4994.2   30.52  4995.8   30.25  5005.5   30.44  5005.9    34.3  5012.6   35.59
  5017.2   39.13  5076.2   41.09  5258.6   42.23  5706.3   41.64  5796.3    42.9
  5816.3   42.02  6046.3   41.99  6316.3   42.49  6341.3   43.87  6377.4   43.16
#Mann= 5 , 1 , 0
 3935.20     0.2       0  4701.5     0.1       0  4983.5    0.02       0
  5017.2     0.1       0  5258.6     0.2       0
#XS Ineff= 2 , 0
       0    4975    39.8    5025       0    39.8
Bank Sta=4983.50,5017.20
Exp/Cntr=0.5,0.3