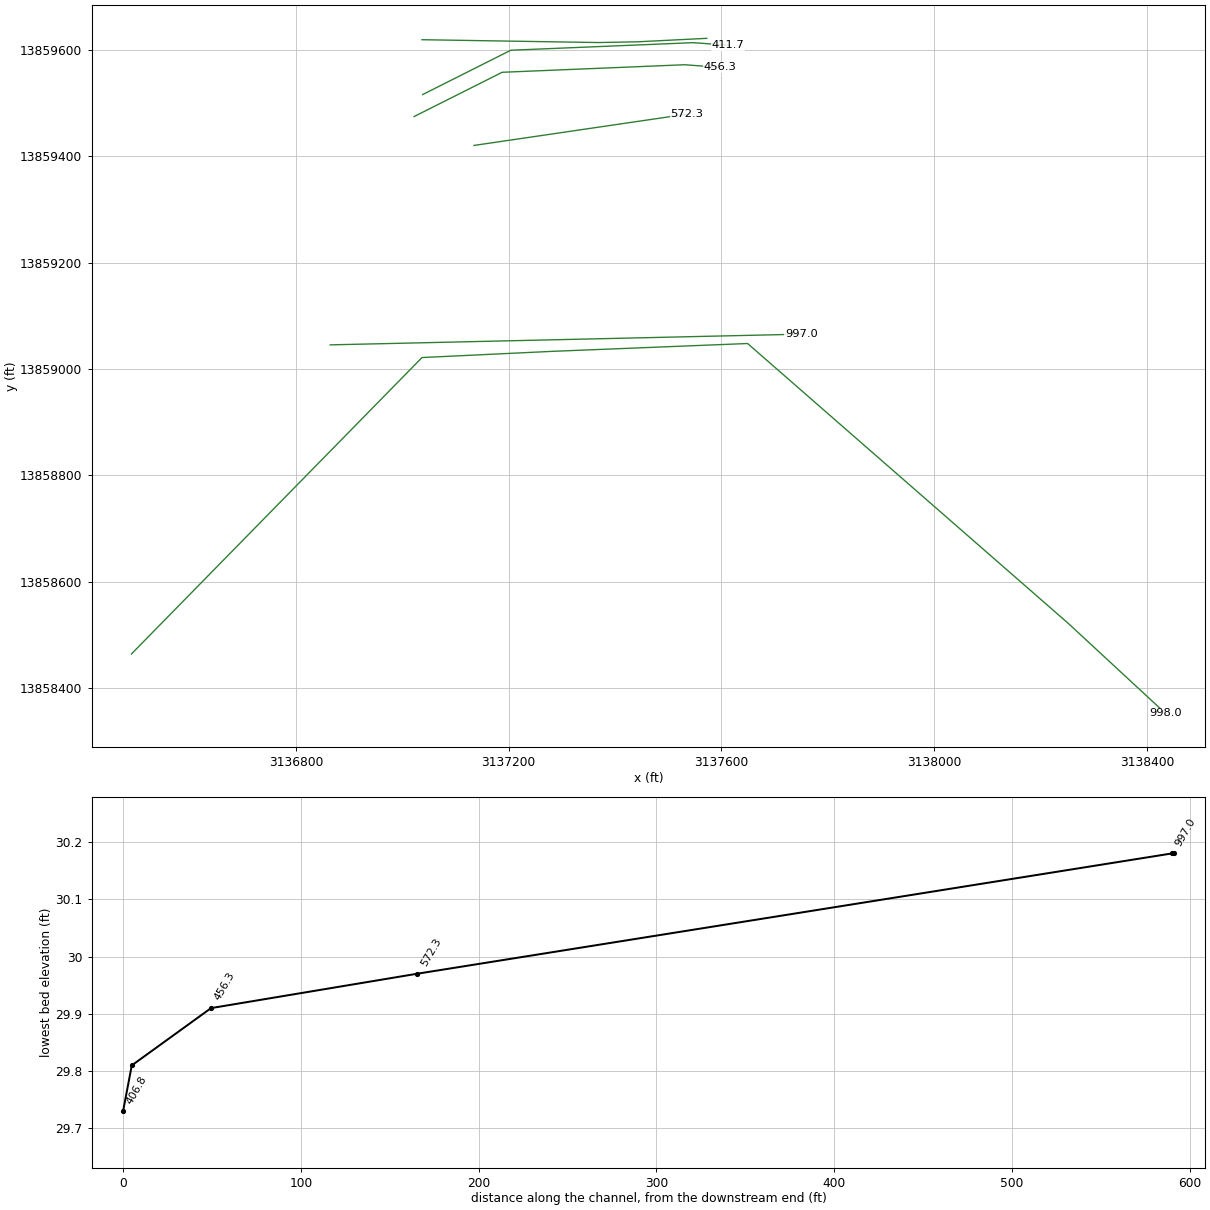
HEC-RAS study H110-00-00.PRJ: H110-00-00

--- H110-00-00.g01 (geometry) --- (continued)

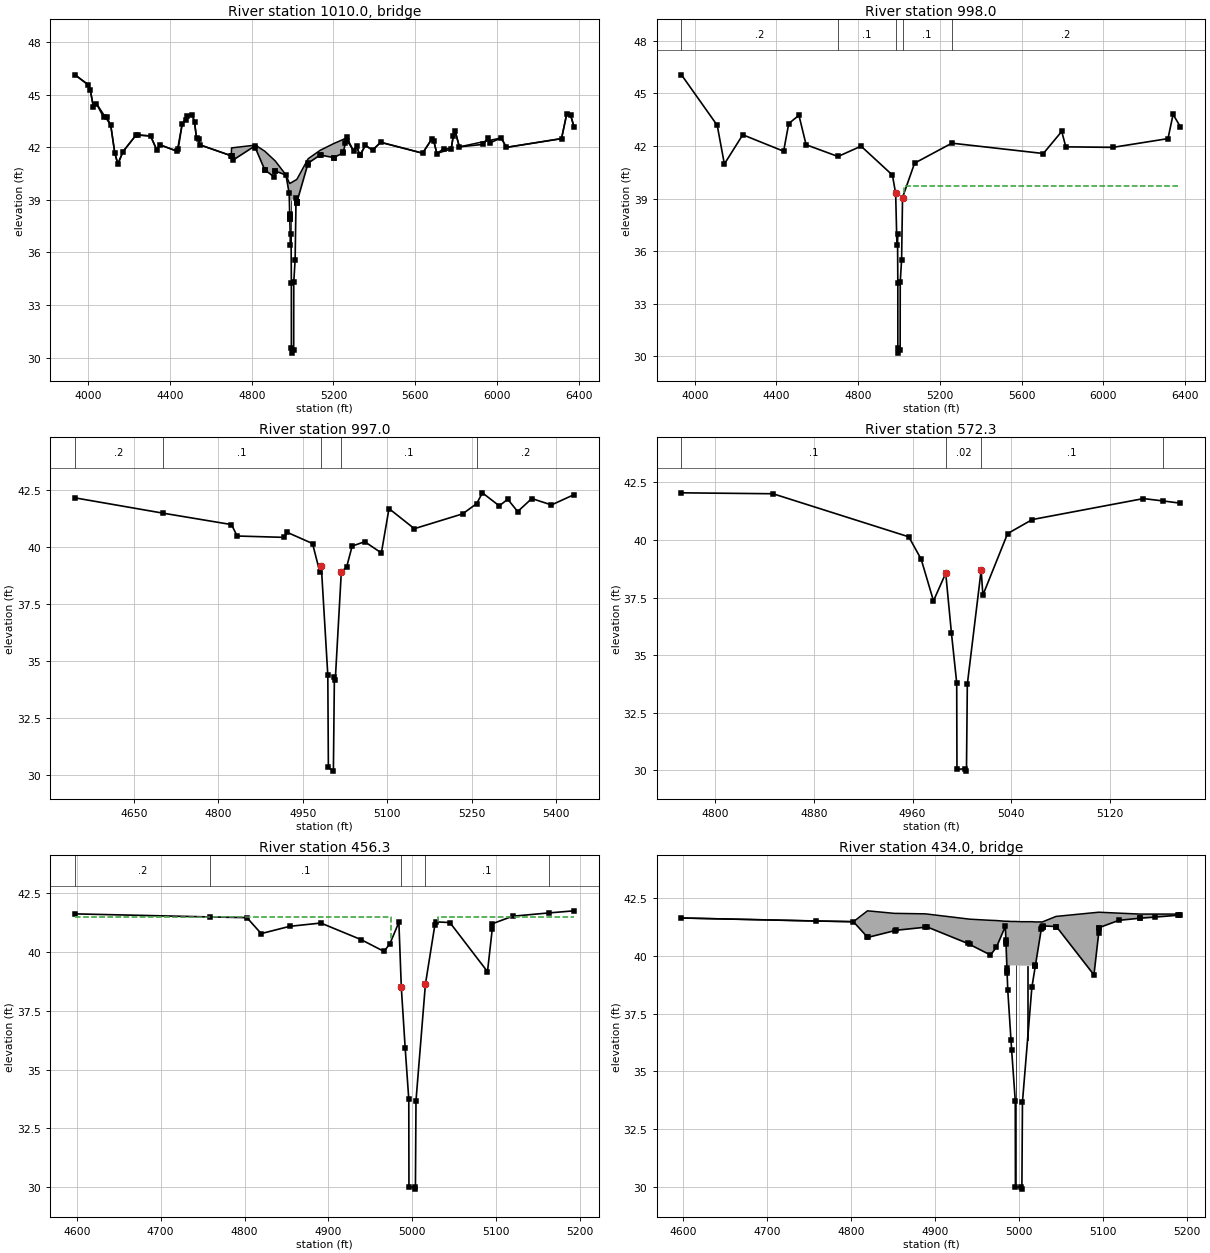
Type RM Length L Ch R = 3 ,1010.0,,,
BEGIN DESCRIPTION:
PARDEE STREET
Structure ID: H10-4
END DESCRIPTION:
Bridge Culvert--1,0,-1,-1, 0
Deck Dist Width WeirC Skew NumUp NumDn MinLoCord MaxHiCord MaxSubmerge Is_Ogee
10,4,2.6,, 60, 60,,,0.95,0,1,1,,
  3935.2  4000.2  4010.2  4025.2  4040.2  4110.2  4130.2  4145.2  4170.2  4235.2
  4305.2  4335.2  4350.2  4435.2  4460.2  4485.2  4510.2  4520.2  4530.2  4540.2
  4545.2  4700.2  4701.4  4708.1  4818.3  4864.3  4910.3  4915.7  4967.7  4983.5
    4986  4986.4  4986.5 5020.59  5020.8  5076.2  5134.4  5201.8  5247.2  5265.2
  5298.6  5313.6  5328.6  5356.3  5391.3  5431.3  5636.3  5681.3  5691.3  5706.3
  5776.3  5786.3  5796.3  5816.3  6021.3  6046.3  6316.3  6341.3  6361.3  6377.4
   46.13   45.56   45.25   44.31   44.49   43.25   41.65   41.04   41.75   42.71
   42.64   41.85   42.14   41.77   43.35   43.79   43.82   43.42   42.51   42.49
   42.14   41.51   41.96   41.97   42.12   41.77   41.27   41.21   40.42   39.98
   39.93   39.93   39.93   40.16   40.16   41.34   41.82   42.21   42.44   42.56
   41.79   42.08   41.54   42.11   41.83   42.28   41.66   42.46   42.34   41.64
    41.9   42.62    42.9   42.02   42.53   41.99   42.49   43.87   43.81   43.16
   46.13   45.56   45.25   44.31   44.49   43.25   41.65   41.04   41.75   42.71
   42.64   41.85   42.14   41.77   43.35   43.79   43.82   43.42   42.51   42.49
   42.14   41.51   41.47   41.26   41.95    40.7    40.3   40.64   40.41   39.36
   38.17   37.98   38.93   39.16   38.85   41.09   41.55   41.41   41.67   42.56
   41.79   42.08   41.54   42.11   41.83   42.28   41.66   42.46   42.34   41.64
    41.9   42.62    42.9   42.02   42.53   41.99   42.49   43.87   43.81   43.16
  3935.2  4000.2  4010.2  4025.2  4040.2  4110.2  4130.2  4145.2  4170.2  4235.2
  4305.2  4335.2  4350.2  4435.2  4460.2  4485.2  4510.2  4520.2  4530.2  4540.2
  4545.2  4700.2  4701.4  4708.1  4818.3  4864.3  4910.3  4915.7  4967.7  4983.5
    4986  4986.4  4986.5 5020.59  5020.8  5076.2  5134.4  5201.8  5247.2  5265.2
  5298.6  5313.6  5328.6  5356.3  5391.3  5431.3  5636.3  5681.3  5691.3  5706.3
  5776.3  5786.3  5796.3  5816.3  6021.3  6046.3  6316.3  6341.3  6361.3  6377.4
   46.13   45.56   45.25   44.31   44.49   43.25   41.65   41.04   41.75   42.71
   42.64   41.85   42.14   41.77   43.35   43.79   43.82   43.42   42.51   42.49
   42.14   41.51   41.96   41.97   42.12   41.77   41.27   41.21   40.42   39.98
   39.93   39.93   39.93   40.16   40.16   41.34   41.82   42.21   42.44   42.56
   41.79   42.08   41.54   42.11   41.83   42.28   41.66   42.46   42.34   41.64
    41.9   42.62    42.9   42.02   42.53   41.99   42.49   43.87   43.81   43.16
   45.96   45.39   45.08   44.14   44.32   43.08   41.48   40.87   41.58   42.54
   42.47   41.68   41.97    41.6   43.18   43.62   43.65   43.25   42.34   42.32
   41.97   41.34    41.3   41.09   41.78   40.53   40.13   40.47   40.24   39.19
      38   37.81   38.76   38.99   38.68   40.92   41.38   41.24    41.5   42.39
   41.62   41.91   41.37   41.94   41.66   42.11   41.49   42.29   42.17   41.47
   41.73   42.45   42.73   41.85   42.36   41.82   42.32    43.7   43.64   42.99
Pier Skew, UpSta & Num, DnSta & Num=,4992.7, 2 ,4992.7, 2 , 0 , 0 , 0 ,,
     0.5     0.5
   35.53   39.97
     0.5     0.5
   35.36    39.8
Pier Skew, UpSta & Num, DnSta & Num=,5012.6, 2 ,5012.6, 2 , 0 , 0 , 0 ,,
     0.5     0.5
   34.54   40.11
     0.5     0.5
   34.37   39.94
BR Coef= 1 , 1 , 0 ,1.25, 0 ,,,0.8,-1,2,0,
Wspro=,,,, 1 ,,,, 0 ,,,, 0 ,,,,-1 ,-1 ,-1 , 0 , 0 , 0 , 0 , 0
BC Design=,, 0 ,, 0 ,,,,,,
BR U #Sta/Elev= 99
  3935.2   46.13  4000.2   45.56  4010.2   45.25  4025.2   44.31  4040.2   44.49
  4075.2   43.71  4090.2   43.73  4110.2   43.25  4130.2   41.65  4145.2   41.04
  4170.2   41.75  4235.2   42.71  4245.2   42.69  4305.2   42.64  4335.2   41.85
  4350.2   42.14  4435.2   41.77  4440.2   41.91  4460.2   43.35  4480.2   43.56
  4485.2   43.79  4510.2   43.82  4520.2   43.42  4530.2   42.51  4540.2   42.49
  4545.2   42.14  4700.2   41.51  4701.4   41.47  4701.5   41.47  4708.1   41.26
  4814.2   42.06  4818.3   41.95  4864.3    40.7  4865.8   40.69  4910.3    40.3
  4915.7   40.64  4916.1   40.64  4967.7   40.41  4983.5   39.36    4986   38.17
 4986.11   38.12 4986.19   38.08  4986.3   38.03  4986.4   37.98  4986.5   37.93
 4986.61   37.88  4989.7   36.41  4992.7   37.02  4994.1   34.26  4994.2   30.52
  4995.8   30.25  5005.5   30.44  5005.9    34.3  5012.6   35.59  5017.2   39.13
  5020.2   38.83  5020.5   38.84 5020.59   38.85  5020.7   38.85  5020.8   38.85
 5021.09   38.87  5021.2   38.87 5021.31   38.87  5073.2   40.97  5076.2   41.09
  5134.4   41.55  5139.8   41.54  5201.6   41.41  5201.8   41.41  5247.2   41.67
  5248.9   41.75  5258.6   42.23  5265.2   42.56  5268.6   42.36  5298.6   41.79
  5313.6   42.08  5328.6   41.54  5331.3   41.54  5356.3   42.11  5391.3   41.83
  5431.3   42.28  5636.3   41.66  5681.3   42.46  5691.3   42.34  5706.3   41.64
  5741.3   41.92  5776.3    41.9  5786.3   42.62  5796.3    42.9  5816.3   42.02
  5931.3   42.16  5956.3    42.5  5966.3   42.25  6021.3   42.53  6046.3   41.99
  6316.3   42.49  6341.3   43.87  6361.3   43.81  6377.4   43.16
BR U #Mann= 5
 3935.20     0.2  4701.5     0.1  4983.5    0.02  5017.2     0.1  5258.6     0.2
BR U Banks=4983.50,5017.20
BR D #Sta/Elev= 99
  3935.2   45.96  4000.2   45.39  4010.2   45.08  4025.2   44.14  4040.2   44.32
  4075.2   43.54  4090.2   43.56  4110.2   43.08  4130.2   41.48  4145.2   40.87
  4170.2   41.58  4235.2   42.54  4245.2   42.52  4305.2   42.47  4335.2   41.68
  4350.2   41.97  4435.2    41.6  4440.2   41.74  4460.2   43.18  4480.2   43.39
  4485.2   43.62  4510.2   43.65  4520.2   43.25  4530.2   42.34  4540.2   42.32
  4545.2   41.97  4700.2   41.34  4701.4    41.3  4701.5    41.3  4708.1   41.09
  4814.2   41.89  4818.3   41.78  4864.3   40.53  4865.8   40.52  4910.3   40.13
  4915.7   40.47  4916.1   40.47  4967.7   40.24  4983.5   39.19    4986      38
 4986.11   37.95 4986.19   37.91  4986.3   37.86  4986.4   37.81  4986.5   37.76
 4986.61   37.71  4989.7   36.24  4992.7   36.85  4994.1   34.09  4994.2   30.35
  4995.8   30.08  5005.5   30.27  5005.9   34.13  5012.6   35.42  5017.2   38.96
  5020.2   38.66  5020.5   38.67 5020.59   38.68  5020.7   38.68  5020.8   38.68
 5021.09    38.7  5021.2    38.7 5021.31    38.7  5073.2    40.8  5076.2   40.92
  5134.4   41.38  5139.8   41.37  5201.6   41.24  5201.8   41.24  5247.2    41.5
  5248.9   41.58  5258.6   42.06  5265.2   42.39  5268.6   42.19  5298.6   41.62
  5313.6   41.91  5328.6   41.37  5331.3   41.37  5356.3   41.94  5391.3   41.66
  5431.3   42.11  5636.3   41.49  5681.3   42.29  5691.3   42.17  5706.3   41.47
  5741.3   41.75  5776.3   41.73  5786.3   42.45  5796.3   42.73  5816.3   41.85
  5931.3   41.99  5956.3   42.33  5966.3   42.08  6021.3   42.36  6046.3   41.82
  6316.3   42.32  6341.3    43.7  6361.3   43.64  6377.4   42.99
BR D #Mann= 5
 3935.20     0.2  4701.5     0.1  4983.5    0.02  5017.2     0.1  5258.6     0.2
BR D Banks=4983.50,5017.20

Type RM Length L Ch R = 1 ,998.0,1,1,1
XS GIS Cut Line= 6
      3136491.04     13858464.11      3137037.20     13859021.30
      3137283.45     13859033.03      3137649.38     13859047.69
      3138252.40     13858521.37      3138434.97     13858352.33
BEGIN DESCRIPTION:
Downstream Section of Bridge/Culvert/Weir
END DESCRIPTION:
#Sta/Elev= 30
  3935.2   46.06  4110.2   43.18  4145.2   40.97  4235.2   42.64  4435.2    41.7
  4460.2   43.28  4510.2   43.75  4545.2   42.07  4701.5    41.4  4814.2   41.99
  4967.7   40.34  4983.5   39.29  4989.7   36.34  4992.7   36.95  4994.1   34.19
  4994.2   30.45  4995.8   30.18  5005.5   30.37  5005.9   34.23  5012.6   35.52
  5017.2   39.06  5076.2   41.02  5258.6   42.16  5706.3   41.57  5796.3   42.83
  5816.3   41.95  6046.3   41.92  6316.3   42.42  6341.3    43.8  6377.4   43.09
#Mann= 5 , 1 , 0
 3935.20     0.2       0  4701.5     0.1       0  4983.5    0.02       0
  5017.2     0.1       0  5258.6     0.2       0
#XS Ineff= 2 , 0
       0    4975    39.7    5025       0    39.7
Bank Sta=4983.50,5017.20
Exp/Cntr=0.5,0.3

Type RM Length L Ch R = 1 ,997.0,417.6,424.7,429.3
XS GIS Cut Line= 2
      3136864.70     13859045.16      3137750.57     13859065.30
BEGIN DESCRIPTION:
Cross Section 997.0
END DESCRIPTION:
#Sta/Elev= 30
  4545.2   42.14  4701.5   41.47  4823.1   40.97  4833.1   40.47  4917.1   40.41
 4922.04   40.63 4967.04   40.14 4979.84    38.9 4982.54   39.17 4994.14   34.38
 4995.14   30.34 5004.04   30.18 5005.84   34.31 5007.44   34.19 5018.14   38.91
 5027.54   39.11 5037.34   40.03 5059.74   40.22 5089.24   39.73  5102.8   41.67
  5147.8   40.79  5233.6   41.44  5258.6   41.89  5268.6   42.36  5298.6   41.79
  5313.6   42.08  5331.3   41.54  5356.3   42.11  5391.3   41.83  5431.3   42.28
#Mann= 5 , 1 , 0
 4545.20     0.2       0  4701.5     0.1       0 4982.54    0.02       0
 5018.14     0.1       0  5258.6     0.2       0
Bank Sta=4982.54,5018.14
Exp/Cntr=0.3,0.1

Type RM Length L Ch R = 1 ,572.3,108.1,116,101.7
XS GIS Cut Line= 2
      3137135.00     13859420.10      3137534.87     13859478.79
BEGIN DESCRIPTION:
Cross Section 572.3 - Interpolated
END DESCRIPTION:
#Sta/Elev= 19
  4772.8   42.05  4846.9   42.01  4956.9   40.14  4966.9   39.17  4976.9   37.36
  4986.8   38.56  4991.4   35.98  4995.7    33.8  4995.9   30.05  5002.6   30.07
  5003.6   29.97  5004.3   33.74  5015.5   38.69  5016.9   37.61  5036.9   40.28
  5056.9   40.89  5146.9    41.8  5162.5    41.7  5176.9    41.6
#Mann= 4 , 1 , 0
 4772.80     0.1       0  4986.8    0.02       0  5015.5     0.1       0
  5162.5     0.2       0
Bank Sta=4986.80,5015.50
Exp/Cntr=0.5,0.3

Type RM Length L Ch R = 1 ,456.3,44.6,44.6,44.6
XS GIS Cut Line= 4
      3137022.28     13859474.34      3137187.91     13859557.61
      3137530.98     13859571.81      3137596.74     13859566.90
BEGIN DESCRIPTION:
Upstream Section of Bridge/Culvert/Weir
END DESCRIPTION:
#Sta/Elev= 27
  4597.9   41.63  4758.3    41.5  4802.8   41.47  4819.8   40.79  4853.8    41.1
  4890.9   41.24  4939.1   40.53  4966.2   40.03  4973.2   40.36  4983.9   41.27
  4986.8    38.5  4991.4   35.92  4995.7   33.74  4995.9   29.99  5002.6   30.01
  5003.6   29.91  5004.3   33.68  5015.5   38.63  5026.7   41.14  5028.7   41.29
  5044.7   41.26  5089.5   39.17  5095.2   40.99  5095.3   41.21  5119.4   41.53
  5162.5   41.67  5192.6   41.76
#Mann= 5 , 1 , 0
 4597.90     0.2       0  4758.3     0.1       0  4986.8    0.02       0
  5015.5     0.1       0  5162.5     0.2       0
#XS Ineff= 2 , 0
       0    4975    41.5    5030       0    41.5
Bank Sta=4986.80,5015.50
Exp/Cntr=0.5,0.3

Type RM Length L Ch R = 3 ,434.0,,,
BEGIN DESCRIPTION:
MIDEN STREET
Structure ID: H10-2
END DESCRIPTION:
Bridge Culvert--1,0,-1,-1, 0
Deck Dist Width WeirC Skew NumUp NumDn MinLoCord MaxHiCord MaxSubmerge Is_Ogee
10,24.6,2.6,,51,51,,,0.95,0,1,1,,
  4597.9  4758.3  4802.8  4819.6  4819.8  4851.8  4853.8  4888.2  4890.9  4939.1
  4941.2  4966.2  4973.2  4983.9 4984.51  4984.6  4984.7 4985.79  4985.9 4986.01
  4986.8  4990.6  4991.4  4995.7  4995.9  5002.6  5003.6  5004.3  5015.5  5019.6
 5019.69  5019.8  5026.7 5027.99  5028.1 5028.21  5028.6  5028.7  5044.4  5044.7
  5089.5  5095.2  5095.3  5095.4  5119.4  5144.2  5144.6  5162.5  5190.1  5190.4
  5192.6
   41.63    41.5   41.47   41.94   41.94   41.83   41.83   41.81    41.8   41.59
   41.58   41.53   41.52   41.49   41.49   41.49   41.49   41.49   41.49   41.49
   41.49   41.48   41.48   41.48   41.48   41.47   41.47   41.47   41.47   41.46
   41.46   41.46   41.46   41.46   41.46   41.46   41.47   41.47    41.7    41.7
   41.86   41.88   41.88   41.88   41.84    41.8    41.8    41.8    41.8   41.83
   41.76
   41.63    41.5   41.47    40.8   40.79   41.08    41.1   41.23   41.24   40.53
   40.49   40.03   40.36   41.27   40.69    40.6   40.51   39.59   39.59   39.59
   39.59   39.58   39.58   39.58   39.58   39.57   39.57   39.57   39.57   39.56
   39.57   39.59   41.14   41.21   41.22   41.23   41.25   41.29   41.26   41.26
   39.17   40.99   41.21   41.21   41.53   41.62   41.62   41.67   41.75   41.75
   41.76
  4597.9  4758.3  4802.8  4819.6  4819.8  4851.8  4853.8  4888.2  4890.9  4939.1
  4941.2  4966.2  4973.2  4983.9 4984.51  4984.6  4984.7 4985.79  4985.9 4986.01
  4986.8  4990.6  4991.4  4995.7  4995.9  5002.6  5003.6  5004.3  5015.5  5019.6
 5019.69  5019.8  5026.7 5027.99  5028.1 5028.21  5028.6  5028.7  5044.4  5044.7
  5089.5  5095.2  5095.3  5095.4  5119.4  5144.2  5144.6  5162.5  5190.1  5190.4
  5192.6
   41.72   41.59   41.56   41.94   41.94   41.83   41.83   41.81    41.8   41.59
   41.58   41.53   41.52   41.49   41.49   41.49   41.49   41.49   41.49   41.49
   41.49   41.48   41.48   41.48   41.48   41.47   41.47   41.47   41.47   41.46
   41.46   41.46   41.46   41.46   41.46   41.46   41.47   41.47    41.7    41.7
   41.86   41.88   41.88   41.88   41.84    41.8    41.8    41.8   41.84   41.84
   41.85
   41.72   41.59   41.56   40.89   40.88   41.17   41.19   41.32   41.33   40.62
   40.58   40.12   40.45   41.36   40.78   40.69    40.6   39.68   39.68   39.68
   39.68   39.67   39.67   39.67   39.67   39.66   39.66   39.66   39.66   39.65
   39.66   39.68   41.23    41.3   41.31   41.32   41.34   41.38   41.35   41.35
   39.26   41.08    41.3    41.3   41.62   41.71   41.71   41.76   41.84   41.84
   41.85
Pier Skew, UpSta & Num, DnSta & Num=,4996.6, 2 ,4996.6, 2 , 0 , 0 , 0 ,,
       1       1
   28.99   40.58
       1       1
   29.08   40.67
Pier Skew, UpSta & Num, DnSta & Num=,5010.4, 2 ,5010.4, 2 , 0 , 0 , 0 ,,
       1       1
   35.15   40.57
       1       1
   35.24   40.66
BR Coef= 1 , 1 , 0 ,1.25, 0 ,,,0.8,0,2,0,
Wspro=,,,, 1 ,,,, 0 ,,,, 0 ,,,,-1 ,-1 ,-1 , 0 , 0 , 0 , 0 , 0
BC Design=,, 0 ,, 0 ,,,,,,
BR U #Sta/Elev= 51
  4597.9   41.63  4758.3    41.5  4802.8   41.47  4819.6    40.8  4819.8   40.79
  4851.8   41.08  4853.8    41.1  4888.2   41.23  4890.9   41.24  4939.1   40.53
  4941.2   40.49  4966.2   40.03  4973.2   40.36  4983.9   41.27 4984.51   40.69
  4984.6    40.6  4984.7   40.51 4985.79   39.46  4985.9   39.36 4986.01   39.25
  4986.8    38.5  4990.6   36.37  4991.4   35.92  4995.7   33.74  4995.9   29.99
  5002.6   30.01  5003.6   29.91  5004.3   33.68  5015.5   38.63  5019.6   39.55
 5019.69   39.57  5019.8   39.59  5026.7   41.14 5027.99   41.21  5028.1   41.22
 5028.21   41.23  5028.6   41.25  5028.7   41.29  5044.4   41.26  5044.7   41.26
  5089.5   39.17  5095.2   40.99  5095.3   41.21  5095.4   41.21  5119.4   41.53
  5144.2   41.62  5144.6   41.62  5162.5   41.67  5190.1   41.75  5190.4   41.75
  5192.6   41.76
BR U #Mann= 5
 4597.90     0.2  4758.3     0.1  4986.8    0.02  5015.5     0.1  5162.5     0.2
BR U Banks=4986.80,5015.50
BR D #Sta/Elev= 51
  4597.9   41.72  4758.3   41.59  4802.8   41.56  4819.6   40.89  4819.8   40.88
  4851.8   41.17  4853.8   41.19  4888.2   41.32  4890.9   41.33  4939.1   40.62
  4941.2   40.58  4966.2   40.12  4973.2   40.45  4983.9   41.36 4984.51   40.78
  4984.6   40.69  4984.7    40.6 4985.79   39.55  4985.9   39.45 4986.01   39.34
  4986.8   38.59  4990.6   36.46  4991.4   36.01  4995.7   33.83  4995.9   30.08
  5002.6    30.1  5003.6      30  5004.3   33.77  5015.5   38.72  5019.6   39.64
 5019.69   39.66  5019.8   39.68  5026.7   41.23 5027.99    41.3  5028.1   41.31
 5028.21   41.32  5028.6   41.34  5028.7   41.38  5044.4   41.35  5044.7   41.35
  5089.5   39.26  5095.2   41.08  5095.3    41.3  5095.4    41.3  5119.4   41.62
  5144.2   41.71  5144.6   41.71  5162.5   41.76  5190.1   41.84  5190.4   41.84
  5192.6   41.85
BR D #Mann= 5
 4597.90     0.2  4758.3     0.1  4986.8    0.02  5015.5     0.1  5162.5     0.2
BR D Banks=4986.80,5015.50

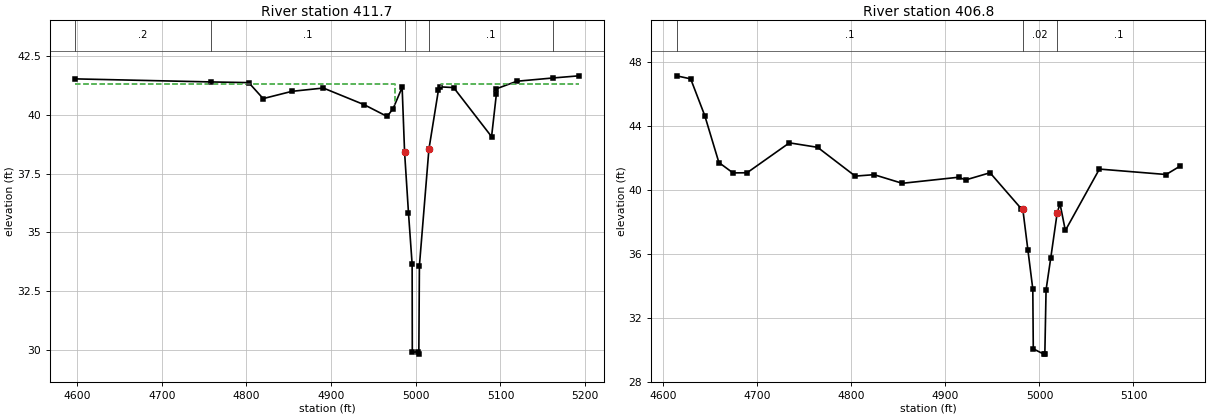
Type RM Length L Ch R = 1 ,411.7,4.9,4.9,4.9
XS GIS Cut Line= 4
      3137038.61     13859515.84      3137204.25     13859599.11
      3137547.32     13859613.31      3137613.08     13859608.41
BEGIN DESCRIPTION:
Downstream Section of Bridge/Culvert/Weir
END DESCRIPTION:
#Sta/Elev= 27
  4597.9   41.53  4758.3    41.4  4802.8   41.37  4819.8   40.69  4853.8      41
  4890.9   41.14  4939.1   40.43  4966.2   39.93  4973.2   40.26  4983.9   41.17
  4986.8    38.4  4991.4   35.82  4995.7   33.64  4995.9   29.89  5002.6   29.91
  5003.6   29.81  5004.3   33.58  5015.5   38.53  5026.7   41.04  5028.7   41.19
  5044.7   41.16  5089.5   39.07  5095.2   40.89  5095.3   41.11  5119.4   41.43
  5162.5   41.57  5192.6   41.66
#Mann= 5 , 1 , 0
 4597.90     0.2       0  4758.3     0.1       0  4986.8    0.02       0
  5015.5     0.1       0  5162.5     0.2       0
#XS Ineff= 2 , 0
       0    4975    41.3    5030       0    41.3
Bank Sta=4986.80,5015.50
Exp/Cntr=0.5,0.3

Type RM Length L Ch R = 1 ,406.8,0,0,0
XS GIS Cut Line= 4
      3137037.11     13859618.87      3137368.85     13859613.53
      3137442.66     13859614.93      3137572.49     13859621.45
BEGIN DESCRIPTION:
Cross Section 406.8
END DESCRIPTION:
#Sta/Elev= 29
  4614.1   47.13  4629.1   46.94  4644.1   44.64  4659.1   41.71  4674.1   41.06
  4689.1   41.07  4734.1   42.94  4764.1   42.66  4804.1   40.86  4824.1   40.95
  4854.1   40.41  4914.1   40.79 4921.43   40.62 4947.43   41.07 4980.83   38.81
 4982.23   38.82 4987.73   36.23 4992.93    33.8 4993.43   30.06 5004.63   29.73
 5005.73   29.76 5007.03   33.75 5012.03   35.75 5018.83   38.55 5021.83   39.14
 5027.53   37.46 5063.73    41.3  5134.7   40.96  5149.7   41.49
#Mann= 3 , 1 , 0
 4614.10     0.1       0 4982.23    0.02       0 5018.83     0.1       0
Bank Sta=4982.23,5018.83
Exp/Cntr=0.3,0.1

Chan Stop Cuts=-1